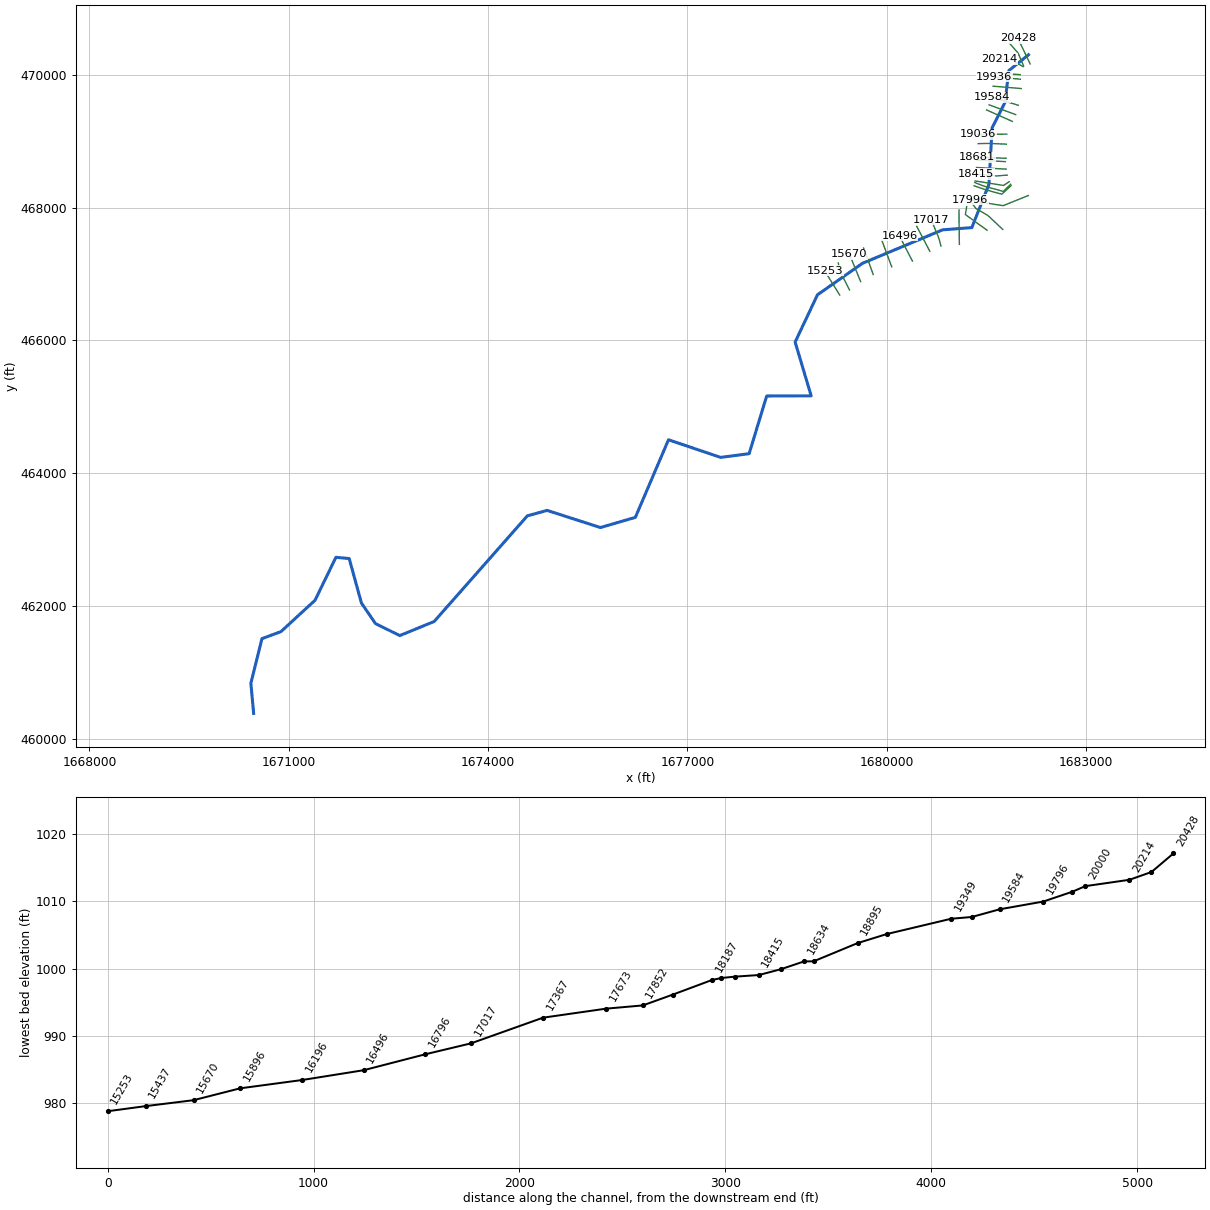
--- HrtRn.prj (project) ---

Proj Title=HrtRn
Current Plan=p01
Default Exp/Contr=0,0
English Units
Geom File=g01
Flow File=f01
Plan File=p01
BEGIN DESCRIPTION:
---------- MODELED AS PART OF WVEM CTP PROGRAM, 2025----------
Stream Name: Hart Run
Flood Zone: AFH
Marshall County, WV
HEC-RAS Version: RAS 6.6
Vertical Datum: NAVD88
Projection: NAD 1983 StatePlane West Virginia N FIPS 4701 (US Feet)
Terrain: 1-meter West Virginia FEMA R3 South Central (collected 2018-2019)
Land Use: 2024 NLCD
Hydrologic Method:
Duda et al., "Estimation of magnitude and frequency of floods for rural, unregulated streams in and near Virginia and West Virginia." September 8, 2025.
Additional Model Notes:
None
END DESCRIPTION:
DSS Export Rating Curves= 0
DSS Export Rating Curve Sorted= 0
DSS Export Volume Flow Curves= 0
DXF OffsetX= 0
DXF OffsetY= 0
DXF ScaleX= 0
DXF ScaleY= 0

--- HrtRn.p01 (plan) ---

Plan Title=Floodplain
Program Version=6.60
Short Identifier=Floodplain
Geom File=g01
Flow File=f01
Subcritical Flow
K Sum by GR= 0
Std Step Tol= 0.01
Critical Tol= 0.01
Num of Std Step Trials= 20
Max Error Tol= 0.3
Flow Tol Ratio= 0.001
Split Flow NTrial= 30
Split Flow Tol= 0.02
Split Flow Ratio= 0.02
Log Output Level= 0
Friction Slope Method= 1
Unsteady Friction Slope Method= 2
Unsteady Bridges Friction Slope Method= 1
Parabolic Critical Depth
Global Vel Dist= 0 , 0 , 0
Global Log Level= 0
CheckData=False
Encroach Param=-1 ,0,0, 0
Flow Ratio Tolerance=0.1
Flow Ratio Min Ratio=0.5
Flow Ratio Max Ratio=4
Flow Ratio Max Iterations= 10
Mapping Interval=1HOUR
Computation Time Step Use Courant=        0
Computation Time Step Use Time Series=    0
Computation Time Step Count To Double=0
Computation Time Step Max Doubling=0
Computation Time Step Max Halving=0
Computation Time Step Residence Courant=0
Run HTab= 0
Run UNet= 0
Run Sediment= 0
Run PostProcess= 0
Run WQNet= 0
Run RASMapper=-1
UNET Theta= 0
UNET Theta Warmup= 0
UNET ZTol= 0
UNET ZSATol= 0
UNET MxIter= 0
UNET Max Iter WO Improvement= 0
UNET MaxInSteps= 0
UNET DtIC= 0
UNET DtMin= 0
UNET MaxCRTS= 0
UNET WFStab= 0
UNET SFStab= 0
UNET WFX= 1
UNET SFX= 1
UNET Gravity=32.17405
UNET 1D Methodology=Finite Difference
UNET DSS MLevel= 1
UNET Pardiso=0
UNET DZMax Abort= 0
UNET Use Existing IB Tables= 0
UNET Froude Reduction=False
UNET Froude Limit= 0
UNET Froude Power= 0
UNET D1 Cores= 0
UNET WindReference=Eulerian
UNET WindDragFormulation=Hsu (1988)
UNET D2 Coriolis=0
UNET D2 Cores= 0
UNET D2 Theta= 1
UNET D2 Theta Warmup= 1
UNET D2 Z Tol= 0.01
UNET D2 Volume Tol= 0.01
UNET D2 Max Iterations= 20
UNET D2 Advanced Convergence=0
UNET D2 WS Max Tol=0.15
UNET D2 WS RMS Tol=0.002
UNET D2 WS Stall Tol=1
UNET D2 Equation= 0
UNET D2 RampUpFraction=0.1
UNET D2 TimeSlices= 1
UNET D2 Turbulence Formulation=Non-Conservative (original)
UNET D2 Eddy Viscosity=0.3
UNET D2 Transverse Eddy Viscosity=0.1
UNET D2 Smagorinsky Mixing=0
UNET D2 BCVolumeCheck=0
UNET D2 Cores=0
UNET D2 SolverType=PARDISO (Direct)
UNET D2 Minimum Iterations= 3
UNET D2 Maximum Iterations= 30
UNET D2 Restart Number= 10
UNET D2 Relaxation Coeff=1.3
UNET D2 SOR Precondition Iterations= 10
UNET D2 ILUT Maximum Fill= 8
UNET D2 ILUT Tolerance=1E-08
UNET D2 Convergence Tolerance=0.00001
PS Theta= 1
PS WS Tol= 0.01
PS Volume Tol= 0.01
PS Max Iterations= 20
PS Equation= 0
PS Advance Time Step=-1
PS Target Courant=0.9
PS Time Slices= 1
PS Iterate With 2D=0
PS Project Initial WSE from DS=-1
PS Ramp Up Initial WSE from US=-1
PS Cores=0
UNET D1D2 MaxIter= 0
UNET D1D2 ZTol=0.01
UNET D1D2 QTol=0.1
UNET D1D2 MinQTol=1
Write IC File= 0
Write IC File at Fixed DateTime=0
Write IC File at Sim End=0
Echo Input=False
Echo Parameters=False
Echo Output=False
Write Detailed= 0
HDF Write Warmup=0
HDF Write Time Slices=0
HDF Flush=0
HDF Compression= 1
HDF Chunk Size= 1
HDF Spatial Parts= 1
HDF Use Max Rows=0
HDF Fixed Rows= 1
Calibration Method= 0
Calibration Iterations= 20
Calibration Max Change=0.05
Calibration Tolerance=0.2
Calibration Maximum=1.5
Calibration Minimum=0.5
Calibration Optimization Method= 1
WQ AD Non Conservative
WQ ULTIMATE=-1
WQ Max Comp Step=1HOUR
WQ Output Interval=15MIN
WQ Output Selected Increments= 0
WQ Create Restart=0
WQ Fixed Restart=0
WQ System Summary=0
WQ Write To DSS=0
Sorting and Armoring Iterations= 10
XS Update Threshold= 0.02
Bed Roughness Predictor= 0
Processes Affected by Predictor=Sediment Only
Hydraulics Update Threshold= 0.02
Energy Slope Method= 1
Volume Change Method= 1
Sediment Retention Method= 0
Sediment TS Multiplier= 1
Warm Up Method= 0
XS Weighting Method= 0
Number of US Weighted Cross Sections= 1
Number of DS Weighted Cross Sections= 1
Upstream XS Weight=0
Main XS Weight=1
Downstream XS Weight=0
Number of DS XS's Weighted with US Boundary= 1
Upstream Boundary Weight= 1
Weight of XSs Associated with US Boundary= 0
Number of US XS's Weighted with DS Boundary= 1
Downstream Boundary Weight= 0.5
Weight of XSs Associated with DS Boundary= 0.5
Percentile Method= 0
Sediment Output Level= 3
Mass or Volume Output= 0
Output Increment Type= 1
Profile and TS Output Increment= 1
Transport Output Increment 1
XS Output Flag= 0
XS Output Increment= 10
Read HDF5 Sediment Hotstart= 0
Sediment Hotstart Type= 0
Write Gradation File= 0
Read Gradation Hotstart= 0
Write HDF5 File= 1
Write Binary Output= 1
Write DSS Sediment File= 0
DSS Sediment Output Type= 1
SV Curve= 0
Specific Gage Flag= 0
Subcell Erosion Methods= 0
Subcell Deposition Methods= 0
Advection Scheme= 1
Matrix Solver= 0
Implicit Weighting Factor= 1
Maximum Outer Loop Convergence Iterations= 5
Convergence Maximum Absolute= 0.001
Convergence RMSE= 0.0001
Grain Fractions Max Abs Error= 0.001
Max Subgrid Regions= 1
Max Subgrid Length Scale= 3.402823E+38
Initial Layer Thickness= 3
Min Layer Thickness= 0.1
Max Layer Thickness= 6
Number of Layers= 5

--- HrtRn.f01 (steady flow) ---

Flow Title=Flow
Program Version=6.60
Number of Profiles= 1
Profile Names=P100yr
River Rch & RM=HrtRn,Main,20428
    2250
River Rch & RM=HrtRn,Main,17673
    2510
River Rch & RM=HrtRn,Main,11392
    3270
Boundary for River Rch & Prof#=HrtRn,Main            , 1
Up Type= 0
Dn Type= 3
Dn Slope=0.01
DSS Import GetInterval= 0
DSS Import GetPeak= 0
DSS Import FillOption= 0

--- HrtRn.g01 (geometry) ---

Geom Title=Geometry
Program Version=6.60

River Reach=HrtRn           ,Main
Reach XY= 30
1682132.08026789470301.4436096091681834.81229702470062.603170246
     1681778.813      469584.901     1681583.981      469201.196
     1681536.743      468350.918     1681279.166      467698.705
     1680839.118      467665.214     1679633.404      467161.307
     1678956.418      466687.357     1678620.009      465975.242
     1678861.343      465165.811     1678191.906      465163.693
     1677928.101      464295.077     1677499.635      464238.995
     1676714.487      464504.038     1676215.355      463335.436
     1675690.483      463182.854     1674888.022      463440.704
     1674590.577      463358.856     1673187.829       461767.66
     1672670.802      461555.678     1672304.994      461736.997
     1672094.187      462044.904      1671909.57      462716.054
     1671709.943       462734.02     1671395.328      462087.065
     1670883.003      461615.623     1670596.816      461509.581
     1670430.326      460837.553     1670471.758      460384.538

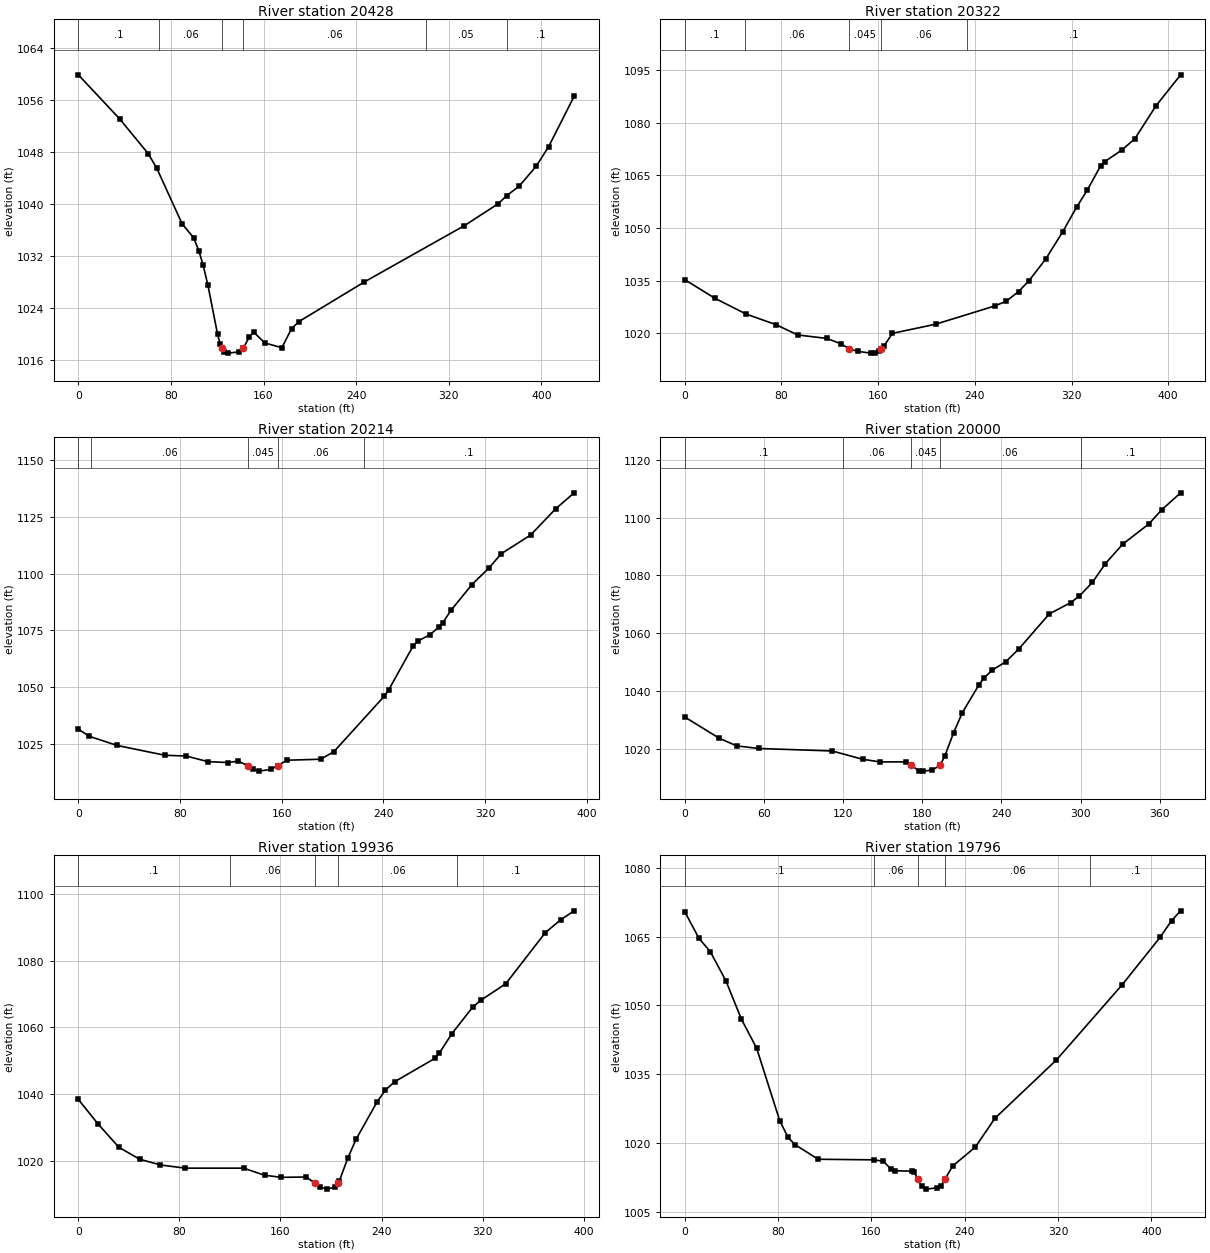
Type RM Length L Ch R = 1 ,20428   ,103.9,106.6,106.2
XS GIS Cut Line= 2
1682157.27325165470162.7200095891681971.69186291470548.730894445
#Sta/Elev= 30
       0 1059.88    35.7 1053.11    60.5 1047.74    67.8 1045.51    89.7 1036.97
    99.6 1034.85   104.2  1032.8   107.8 1030.63   111.9 1027.59   120.3 1019.99
   122.4 1018.59   124.2 1017.93     126 1017.37   129.6 1017.12   138.9 1017.32
  142.651017.903   147.8 1019.66   151.5 1020.35     161 1018.69   175.8 1017.95
   184.2 1020.89   190.5 1021.96   247.1 1028.06   333.5 1036.71   362.6 1040.06
     370 1041.31   380.8 1042.77   395.4 1045.81   406.3 1048.86   428.3 1056.59
#Mann= 6 ,-1,0
       0      .1       0      70     .06       0   124.2    .045       0
  142.65     .06       0     300     .05       0     370      .1       0
Bank Sta=124.2,142.65
XS Rating Curve= 0 ,0
Exp/Cntr(USF)=0,0
Exp/Cntr=0.3,0.1

Type RM Length L Ch R = 1 ,20322   ,98.5,107.5,114.5
XS GIS Cut Line= 3
1682058.52629693470131.2091092911681975.30916229470327.410701059
1681844.85096008470475.294399543
#Sta/Elev= 30
       0 1035.28      25 1029.96    50.7 1025.49    75.6 1022.45    93.4 1019.54
   117.6 1018.54   129.1 1017.03   136.2 1015.58   143.3 1014.85     154 1014.36
   157.6  1014.5   161.1 1015.05  162.661015.605   164.7 1016.33   171.8 1019.99
   207.5 1022.59   256.9 1027.83   266.2 1029.19   276.2  1031.9   284.7 1034.92
   298.8 1041.22   312.7  1048.9   324.3 1055.97   333.1 1060.81   344.2 1067.76
   347.6 1068.91   361.5 1072.16   372.4  1075.4   389.9 1084.78   410.3 1093.61
#Mann= 5 ,-1,0
       0      .1       0      50     .06       0   136.2    .045       0
  162.66     .06       0  233.12      .1       0
Bank Sta=136.2,162.66
XS Rating Curve= 0 ,0
Exp/Cntr(USF)=0,0
Exp/Cntr=0.3,0.1

Type RM Length L Ch R = 1 ,20214   ,207.9,213.9,218.3
XS GIS Cut Line= 3
1682048.66585396470122.7698125741681882.09285191470222.984464212
1681687.08055683470237.881236753
#Sta/Elev= 30
       0 1031.65     8.5 1028.53    30.5 1024.48    68.1 1020.17      85 1019.83
   101.8 1017.37   117.9 1016.97   125.7 1017.62  133.221015.601   137.6 1013.95
   142.4  1013.2   151.4    1014  156.911015.601   163.9 1017.99   190.6 1018.43
     201 1021.74   240.5 1046.04   244.1 1048.88   263.5 1068.39   266.8 1070.23
   276.7 1073.22   283.3 1076.35   286.6 1078.35   293.1 1083.83   309.6 1095.19
   322.8 1102.35   332.7 1108.76   355.7 1116.92   375.5 1128.49     390 1135.49
#Mann= 5 ,-1,0
       0      .1       0      10     .06       0  133.22    .045       0
  156.91     .06       0   224.4      .1       0
Bank Sta=133.22,156.91
XS Rating Curve= 0 ,0
Exp/Cntr(USF)=0,0
Exp/Cntr=0.3,0.1

Type RM Length L Ch R = 1 ,20000   ,64.5,63.9,63.7
XS GIS Cut Line= 2
1682006.68404043470002.2413801981681631.55622281470026.617917083
#Sta/Elev= 30
       0 1030.98    26.3 1023.59    39.4    1021    55.9  1020.1   111.7 1019.24
   134.8 1016.37   147.9 1015.45   167.6 1015.46  171.731014.215   177.5 1012.41
   180.8 1012.26   187.4 1012.62  193.561014.214   197.2 1017.57   203.8 1025.58
   210.4 1032.49   223.1  1042.2   226.8 1044.49   233.1 1047.24   243.3  1050.1
   253.1 1054.48   276.3 1066.67   292.6 1070.59   299.1 1072.85     309 1077.58
   318.9 1084.11     332 1090.82   351.7 1097.77   361.6 1102.73   375.9 1108.59
#Mann= 5 ,-1,0
       0      .1       0     120     .06       0  171.73    .045       0
  193.56     .06       0     300      .1       0
Bank Sta=171.73,193.56
XS Rating Curve= 0 ,0
Exp/Cntr(USF)=0,0
Exp/Cntr=0.3,0.1

Type RM Length L Ch R = 1 ,19936   ,141,140.6,140.5
XS GIS Cut Line= 2
 1682009.1758642469933.6688276881681618.22496564469968.222568722
#Sta/Elev= 30
       0 1038.36    15.6    1031    32.1 1023.99    48.6  1020.4      65 1018.68
    84.8 1017.72   130.9 1017.72   147.4 1015.59   160.6 1014.97   180.3 1015.05
   187.71013.127   191.2  1012.1   196.8 1011.42   203.4  1012.1  205.211013.126
   206.7 1013.97   213.3 1020.71   219.8 1026.35   236.3  1037.5   242.9 1041.12
   250.4 1043.69   282.4 1050.74   285.7 1052.22   295.6 1058.08   312.1 1066.06
   318.6 1068.17   338.4 1073.14   369.7  1088.5   381.8 1092.34   392.5 1095.04
#Mann= 5 ,-1,0
       0      .1       0     120     .06       0   187.7    .045       0
  205.21     .06       0     300      .1       0
Bank Sta=187.7,205.21
XS Rating Curve= 0 ,0
Exp/Cntr(USF)=0,0
Exp/Cntr=0.3,0.1

Type RM Length L Ch R = 1 ,19796   ,214.5,211.8,209.8
XS GIS Cut Line= 6
1682022.19848743469792.4416184281681935.02412109469799.983270004
1681860.30314192469806.4478240011681760.67538843469815.067229345
1681685.95473734469821.5317833421681598.64159176 469827.47041975
#Sta/Elev= 30
       0 1070.41    12.2  1064.6    21.8 1061.75    35.3 1055.33    48.5 1047.02
    61.6 1040.67    81.4 1024.86    88.5 1021.25    94.5 1019.66   114.3 1016.48
   162.5 1016.35   170.3 1016.03   176.9 1014.28   180.2 1013.97   194.6 1013.89
   196.7 1013.63  199.851012.153   203.2 1010.56   206.5 1009.97   216.4 1010.25
   219.7 1010.72  223.091012.157   229.6    1015   249.1 1019.15   265.8  1025.4
   318.5 1038.11     375 1054.54   407.3 1064.81   417.3  1068.5     425 1070.62
#Mann= 5 ,-1,0
       0      .1       0   162.5     .06       0  199.85    .045       0
  223.09     .06       0   347.5      .1       0
Bank Sta=199.85,223.09
XS Rating Curve= 0 ,0
Exp/Cntr(USF)=0,0
Exp/Cntr=0.3,0.1

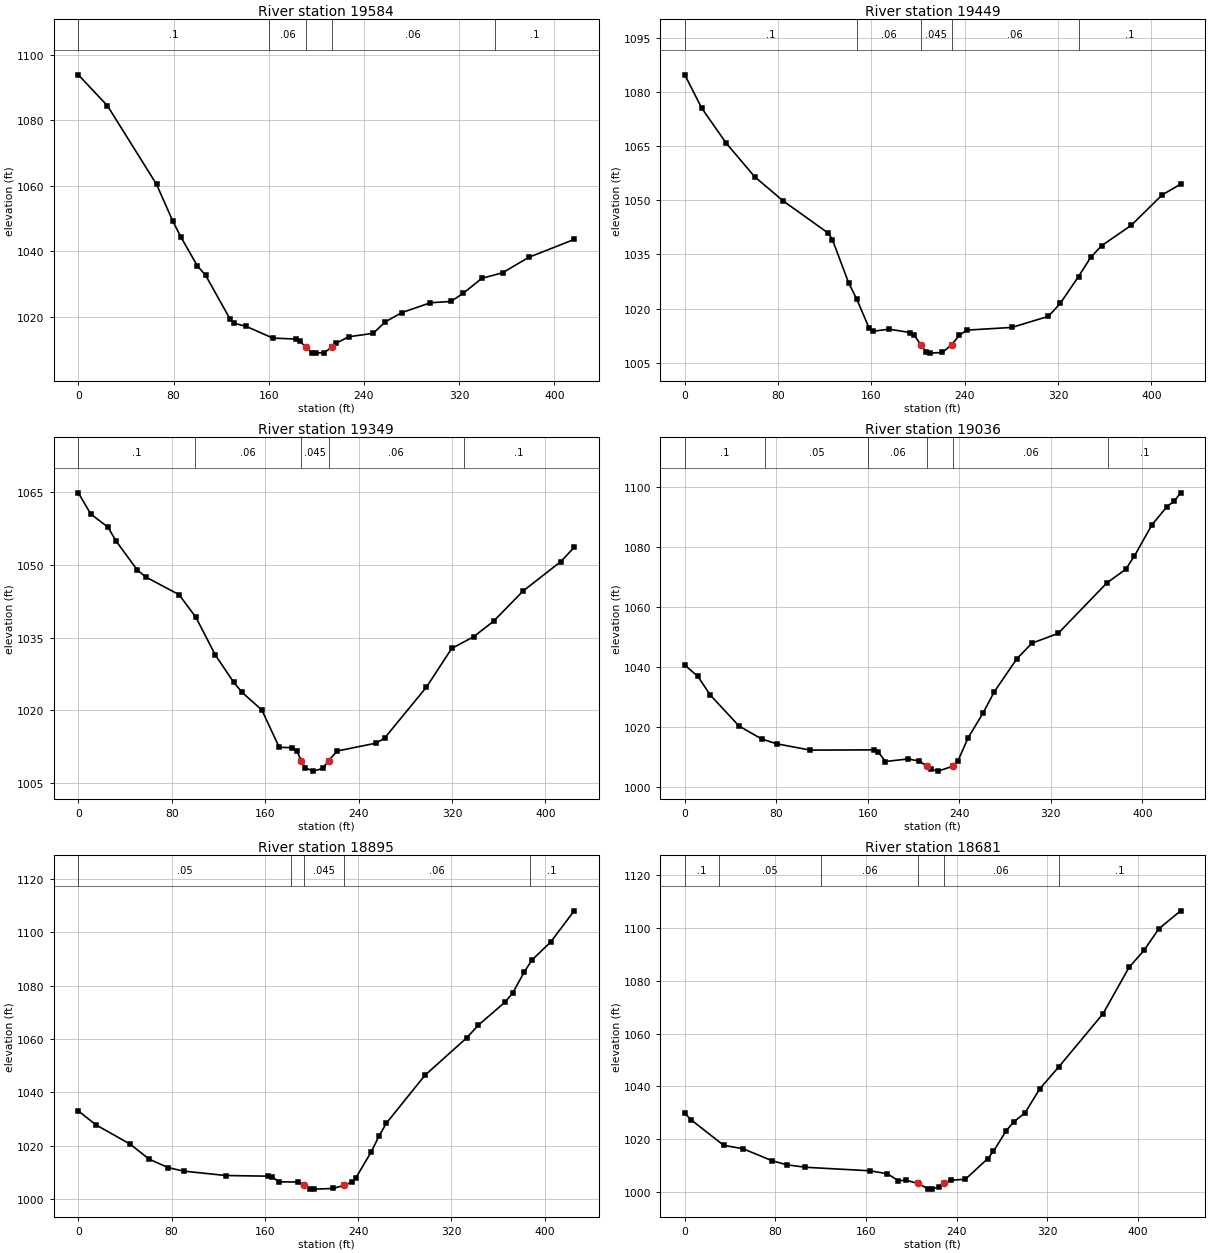
Type RM Length L Ch R = 1 ,19584   ,135.4,134.8,134.5
XS GIS Cut Line= 2
 1681977.5838724469540.7434296371681579.72222563469664.149647618
#Sta/Elev= 30
       0 1093.81    24.5 1084.34    65.7 1060.37    79.4 1049.11    86.3  1044.2
     100 1035.47   106.9 1032.61   127.5 1019.21   130.9 1017.96   141.2 1016.97
   163.4 1013.41   182.5 1013.12   185.9 1012.59  191.381010.545   196.2 1009.01
   199.6 1008.82   206.5 1008.99  212.791010.546   216.8 1011.85   227.1 1013.82
   247.7 1014.86     258 1018.39   271.8 1021.19   295.8  1024.2     313  1024.6
   323.3 1027.06     339 1031.66   356.5 1033.37   378.4 1038.07   416.6 1043.53
#Mann= 5 ,-1,0
       0      .1       0     160     .06       0  191.38    .045       0
  212.79     .06       0     350      .1       0
Bank Sta=191.38,212.79
XS Rating Curve= 0 ,0
Exp/Cntr(USF)=0,0
Exp/Cntr=0.3,0.1

Type RM Length L Ch R = 1 ,19449   ,100.9,100.2,99.5
XS GIS Cut Line= 6
1681938.40750177469400.4974211911681856.28069753469430.687321441
1681785.88615327469456.5645662711681692.02741711469491.067778112
1681621.63287285469516.9450229421681539.50606861469547.134923191
#Sta/Elev= 30
       0 1084.75    14.6 1075.48    35.6 1065.78      60 1056.49    84.2 1049.86
     123  1040.9   126.5 1039.14   140.4 1027.16   147.4 1022.63   157.9 1014.67
   161.4 1013.75   175.4 1014.31   192.9 1013.39   196.4 1012.72  202.34 1010.02
   206.9 1007.94   210.3 1007.68   220.8 1007.87  228.861010.019   235.4 1012.63
   241.8 1014.05   280.3  1014.8   311.7 1017.87   321.9  1021.5   337.5  1028.9
   347.9 1034.18   357.2 1037.41   382.7 1043.08   409.2 1051.51     425 1054.47
#Mann= 5 ,-1,0
       0      .1       0   147.5     .06       0  202.34    .045       0
  228.86     .06       0   337.5      .1       0
Bank Sta=202.34,228.86
XS Rating Curve= 0 ,0
Exp/Cntr(USF)=0,0
Exp/Cntr=0.3,0.1

Type RM Length L Ch R = 1 ,19349   ,306.5,313.5,316.4
XS GIS Cut Line= 2
1681888.73139545469297.8799926511681500.74224612469470.648697824
#Sta/Elev= 30
       0  1064.9    10.6 1060.53    25.3 1057.82    32.5 1054.88    50.4 1048.99
    57.6 1047.54    86.3 1043.86   100.7 1039.19   117.4 1031.38     133  1025.8
   140.2  1023.7   157.2 1020.04   172.1 1012.33   183.3 1012.27   186.9 1011.64
  191.031009.615   194.5 1008.09   201.2 1007.42   209.4 1007.98  214.411009.614
   221.8 1011.58   255.1  1013.2   262.3 1014.23   298.2 1024.78   319.8 1032.75
   338.6 1035.18   355.7 1038.38   380.8 1044.59   413.2 1050.69   424.7 1053.63
#Mann= 5 ,-1,0
       0      .1       0     100     .06       0  191.03    .045       0
  214.41     .06       0     330      .1       0
Bank Sta=191.03,214.41
XS Rating Curve= 0 ,0
Exp/Cntr(USF)=0,0
Exp/Cntr=0.3,0.1

Type RM Length L Ch R = 1 ,19036   ,141.3,140.3,139.4
XS GIS Cut Line= 2
1681804.81516722469106.3535423451681371.41252968469102.404543369
#Sta/Elev= 30
       0 1040.53    11.3 1036.86    22.3 1030.55    47.4 1020.21    67.1  1015.9
    80.2 1014.28   109.8 1012.16   165.6 1012.24   168.8 1011.67   175.4 1008.35
   195.1 1009.21   204.9 1008.52  211.541006.788   214.8 1005.78   221.3 1005.14
  234.431006.786   238.6 1008.43   247.6 1016.23   260.7 1024.55   270.5 1031.65
   290.2 1042.65   303.4 1047.89   326.3 1051.14     369 1068.04   385.4 1072.56
     393 1077.01   408.3 1087.42   421.5 1093.53     428 1095.42   433.4 1098.12
#Mann= 6 ,-1,0
       0      .1       0      70     .05       0     160     .06       0
  211.54    .045       0  234.43     .06       0     370      .1       0
Bank Sta=211.54,234.43
XS Rating Curve= 0 ,0
Exp/Cntr(USF)=0,0
Exp/Cntr=0.3,0.1

Type RM Length L Ch R = 1 ,18895   ,214.3,214.2,214.2
XS GIS Cut Line= 6
1681798.39250459468955.1030700061681710.98454292468959.130949095
1681636.06474526468962.5994460881681536.11907901468966.080410257
1681460.99816626 468965.202787341681373.31789543468963.284484088
#Sta/Elev= 30
       0 1033.09    14.8 1027.95    44.3 1020.69    60.8 1015.01    77.2 1011.84
    90.3 1010.55   126.4 1008.91   162.5 1008.66   165.9 1008.41   172.4 1006.53
   188.8 1006.48  193.441005.183   198.7 1003.91     202 1003.81   218.4 1004.05
  227.751005.182   234.8 1006.51   238.1 1008.04   251.2 1017.73   257.8 1023.59
   264.3 1028.52   297.2 1046.37   333.2 1060.46   343.1 1065.17   366.1 1073.83
   372.6 1077.23   382.5 1085.08   389.1 1089.57   405.2 1096.31   425.3 1107.97
#Mann= 5 ,-1,0
       0     .05       0   182.5     .06       0  193.44    .045       0
  227.75     .06       0  387.63      .1       0
Bank Sta=193.44,227.75
XS Rating Curve= 0 ,0
Exp/Cntr(USF)=0,0
Exp/Cntr=0.3,0.1

Type RM Length L Ch R = 1 ,18681   ,47.3,46.9,46.8
XS GIS Cut Line= 2
1681794.94266979468743.0456366091681357.59103326468757.854382767
#Sta/Elev= 30
       0  1029.8     5.7  1027.3    34.3 1017.69    51.4  1016.4      77 1011.86
    90.1 1010.31   106.5 1009.38   163.5 1008.04   178.7 1006.91   188.6 1004.29
   195.2 1004.47  206.041003.233   214.8 1001.16   218.1  1001.1   224.7 1002.03
   228.41003.234   234.5 1004.44   247.7 1004.86   267.4 1012.66   272.4 1015.43
   283.8 1023.29   290.4  1026.6   300.2 1029.93   313.3 1039.09     330 1047.36
   369.1 1067.51   392.1 1085.08   405.2 1091.47   418.4 1099.71   437.6 1106.49
#Mann= 6 ,-1,0
       0      .1       0      30     .05       0     120     .06       0
  206.04    .045       0   228.4     .06       0     330      .1       0
Bank Sta=206.04,228.4
XS Rating Curve= 0 ,0
Exp/Cntr(USF)=0,0
Exp/Cntr=0.3,0.1

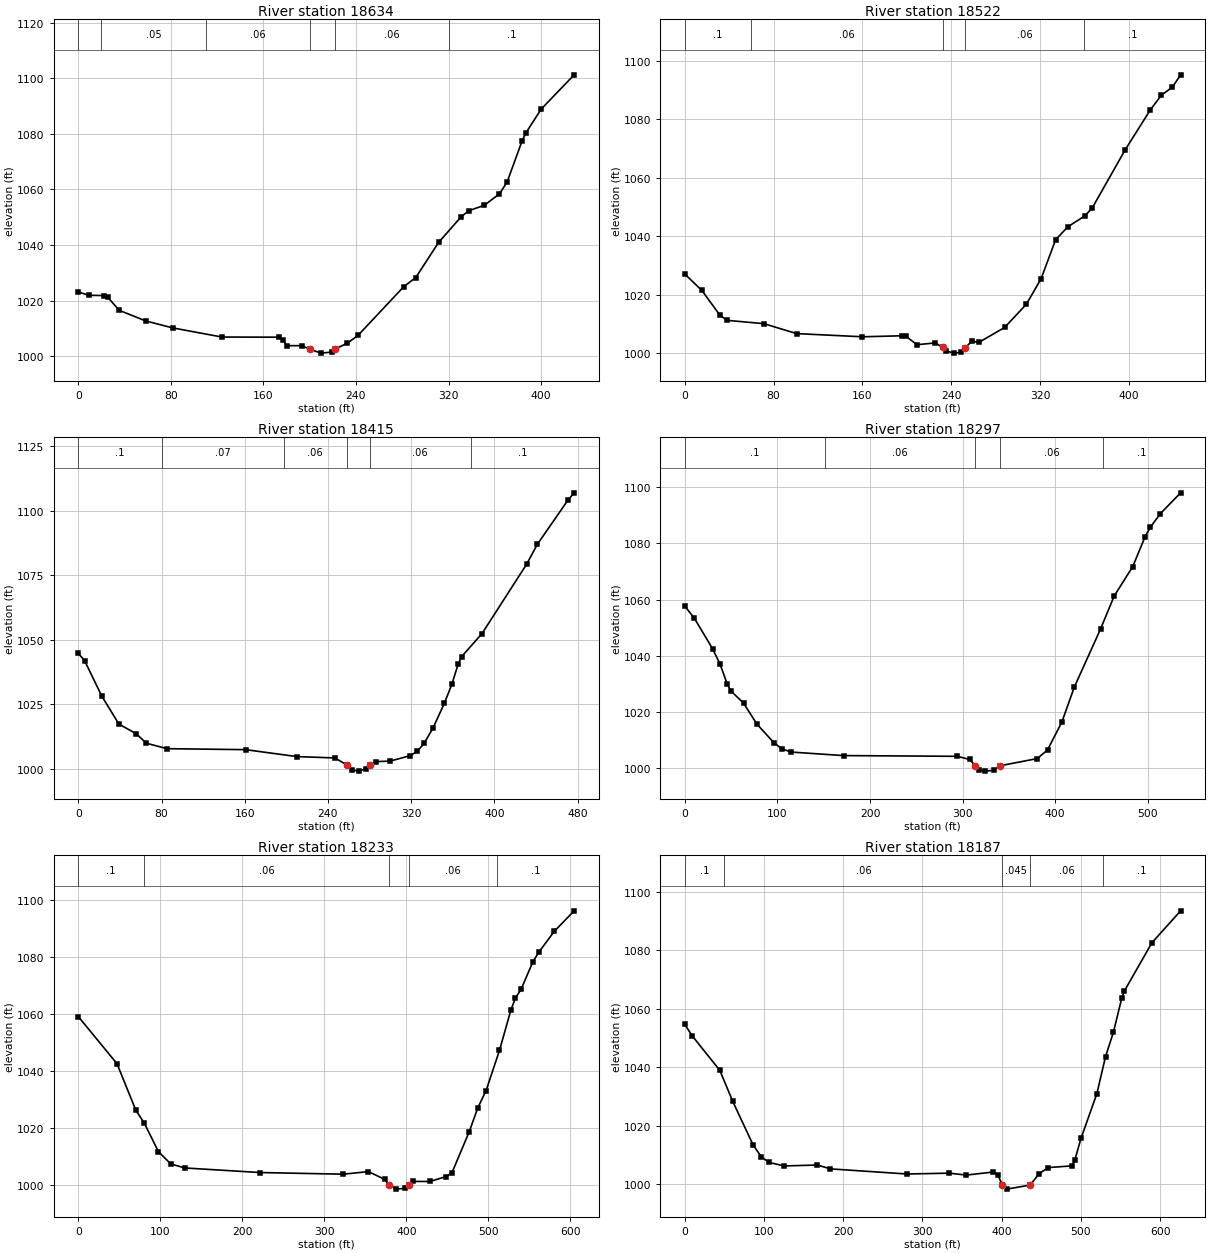
Type RM Length L Ch R = 1 ,18634   ,112.5,111.8,112.3
XS GIS Cut Line= 2
1681782.91283063468692.2296708831681354.94030751468715.572843546
#Sta/Elev= 30
       0 1023.08     9.1 1021.88    22.3  1021.8    25.6  1021.1    35.4 1016.46
    58.4 1012.64    81.4 1010.17   124.1 1006.87   173.4 1006.81   176.7  1005.9
     180 1003.77   193.1 1003.75   200.11002.511   209.6 1001.08   219.4 1001.47
  221.65 1002.52   232.6 1004.65   241.8 1007.47   281.3 1024.99   291.7 1028.28
   311.4 1040.89   331.1 1050.22   337.7 1052.34   350.9 1054.25     364 1058.36
   370.6 1062.59   383.7 1077.55     387 1080.39   400.1 1088.87   428.6  1101.2
#Mann= 6 ,-1,0
       0      .1       0      20     .05       0     110     .06       0
   200.1    .045       0  221.65     .06       0     320      .1       0
Bank Sta=200.1,221.65
XS Rating Curve= 0 ,0
Exp/Cntr(USF)=0,0
Exp/Cntr=0.3,0.1

Type RM Length L Ch R = 1 ,18522   ,107.8,107.6,107
XS GIS Cut Line= 2
1681795.69685598468579.4369407371681349.65742171468604.315634282
#Sta/Elev= 30
       0 1027.02    15.4  1021.4    31.8 1012.84    38.4 1011.15    71.2 1010.03
   100.8 1006.62     160 1005.53   196.1 1005.88   199.4 1005.65   209.2 1002.81
   225.7 1003.43   232.2  1001.9   235.5 1000.67   242.4  999.93   248.7 1000.22
  252.861001.832   258.5 1003.99   265.1 1003.64   288.1 1008.72   307.8 1016.71
     321 1025.43   334.1  1038.8   345.1 1043.22   360.4 1046.95   367.1 1049.69
   396.5 1069.43   419.5 1083.34   429.4 1088.32   439.3 1091.09   446.7 1095.29
#Mann= 5 ,-1,0
       0      .1       0      60     .06       0   232.2    .045       0
  252.86     .06       0     360      .1       0
Bank Sta=232.2,252.86
XS Rating Curve= 0 ,0
Exp/Cntr(USF)=0,0
Exp/Cntr=0.3,0.1

Type RM Length L Ch R = 1 ,18415   ,118.5,117.8,116.7
XS GIS Cut Line= 3
1681812.71316517468489.3224524411681645.86795846468476.488205771
1681337.84603838468505.118448342
#Sta/Elev= 30
       0 1044.69     6.1 1041.81    22.6 1028.09      39 1017.28    55.5 1013.59
    65.4 1009.88    85.1 1007.76   160.8 1007.38   210.2 1004.69   246.5 1004.17
  258.031001.517   262.9  999.56   269.5  999.06   276.1  999.92  279.981001.514
     286 1002.75   299.7 1002.94   318.9 1005.03   325.9 1006.73   332.4 1009.81
     341 1015.76   351.9 1025.32   359.1  1032.7   365.1  1040.4   368.4 1043.37
   388.1 1052.35     431 1079.22   441.3 1086.93   470.5 1103.93   476.7 1106.89
#Mann= 6 ,-1,0
       0      .1       0      80     .07       0  197.34     .06       0
  258.03    .045       0  279.98     .06       0  377.34      .1       0
Bank Sta=258.03,279.98
XS Rating Curve= 0 ,0
Exp/Cntr(USF)=0,0
Exp/Cntr=0.3,0.1

Type RM Length L Ch R = 1 ,18297   ,64.9,63.8,62.3
XS GIS Cut Line= 3
1681841.32488443468390.639732473 1681757.4086562 468333.37924733
1681328.94226737468401.499479656
#Sta/Elev= 30
       0 1057.64    10.3 1053.35    30.1  1042.4    38.1 1036.93      46 1029.72
      50 1027.33    63.4 1023.08    77.8 1015.62    96.4 1008.89   104.9 1006.77
   114.9 1005.62   171.4 1004.36   294.2  1004.1   307.6 1002.98  313.561000.775
   317.6  999.27   324.2  998.82   334.2  999.12   340.51000.743   380.7  1003.3
   391.7  1006.4   407.2 1016.35   420.5  1028.7     449 1049.55   463.7 1061.29
   483.7 1071.75   496.9 1082.31   502.8 1085.84   513.5 1090.63   535.4 1098.06
#Mann= 5 ,-1,0
       0      .1       0  151.59     .06       0  313.56    .045       0
   340.5     .06       0  451.59      .1       0
Bank Sta=313.56,340.5
XS Rating Curve= 0 ,0
Exp/Cntr(USF)=0,0
Exp/Cntr=0.3,0.1

Type RM Length L Ch R = 1 ,18233   ,46.4,46.3,47
XS GIS Cut Line= 5
1681863.27015969468351.4868073511681753.25782077468243.721814129
 1681661.9650994468269.1271363051681457.60440242468324.215672012
1681323.43716224468377.527158179
#Sta/Elev= 30
       0 1059.16    47.2 1042.62    70.2 1026.25    80.3 1021.87    97.7 1011.78
   112.7 1007.47   129.9 1006.05   221.7 1004.44   323.2 1003.86   353.8 1004.77
   373.8 1002.03   378.6 1000.22   387.8  998.62     398  998.88   403.11000.213
   408.2 1001.33   428.6  1001.3     449 1003.05   455.8  1004.4   476.8 1018.77
   487.3 1027.15   497.4 1033.23   513.7 1047.29   527.7 1061.55   533.2 1065.66
   540.3 1068.89   554.4 1078.37   561.5 1081.69   580.7 1089.13   604.8 1096.28
#Mann= 5 ,-1,0
       0      .1       0      80     .06       0   378.6    .045       0
   403.1     .06       0  510.42      .1       0
Bank Sta=378.6,403.1
XS Rating Curve= 0 ,0
Exp/Cntr(USF)=0,0
Exp/Cntr=0.3,0.1

Type RM Length L Ch R = 1 ,18187   ,190.7,191.1,191.9
XS GIS Cut Line= 4
1681869.35523046468330.5198441031681729.85684166468201.683752532
1681481.06990621 468270.100159781681313.13872478468328.742794565
#Sta/Elev= 30
       0 1054.67     9.4 1050.74    44.2 1038.96    60.5 1028.35      86 1013.55
    96.3 1009.47     106 1007.46   125.6 1006.25   167.3 1006.57   183.7 1005.25
   280.4  1003.5   333.9 1003.78   355.4 1003.13   389.3 1004.17   395.3 1003.06
   400.7999.8118   406.3  998.32  436.01 999.722   447.2 1003.63   458.9  1005.7
   488.8 1006.28   492.4 1008.41   500.1 1015.73   520.1 1030.99     531 1043.63
     541 1052.03   551.4 1063.56   554.9 1066.17   589.6 1082.63   625.8 1093.54
#Mann= 5 ,-1,0
       0      .1       0      50     .06       0   400.7    .045       0
  436.01     .06       0  527.91      .1       0
Bank Sta=400.7,436.01
XS Rating Curve= 0 ,0
Exp/Cntr(USF)=0,0
Exp/Cntr=0.3,0.1

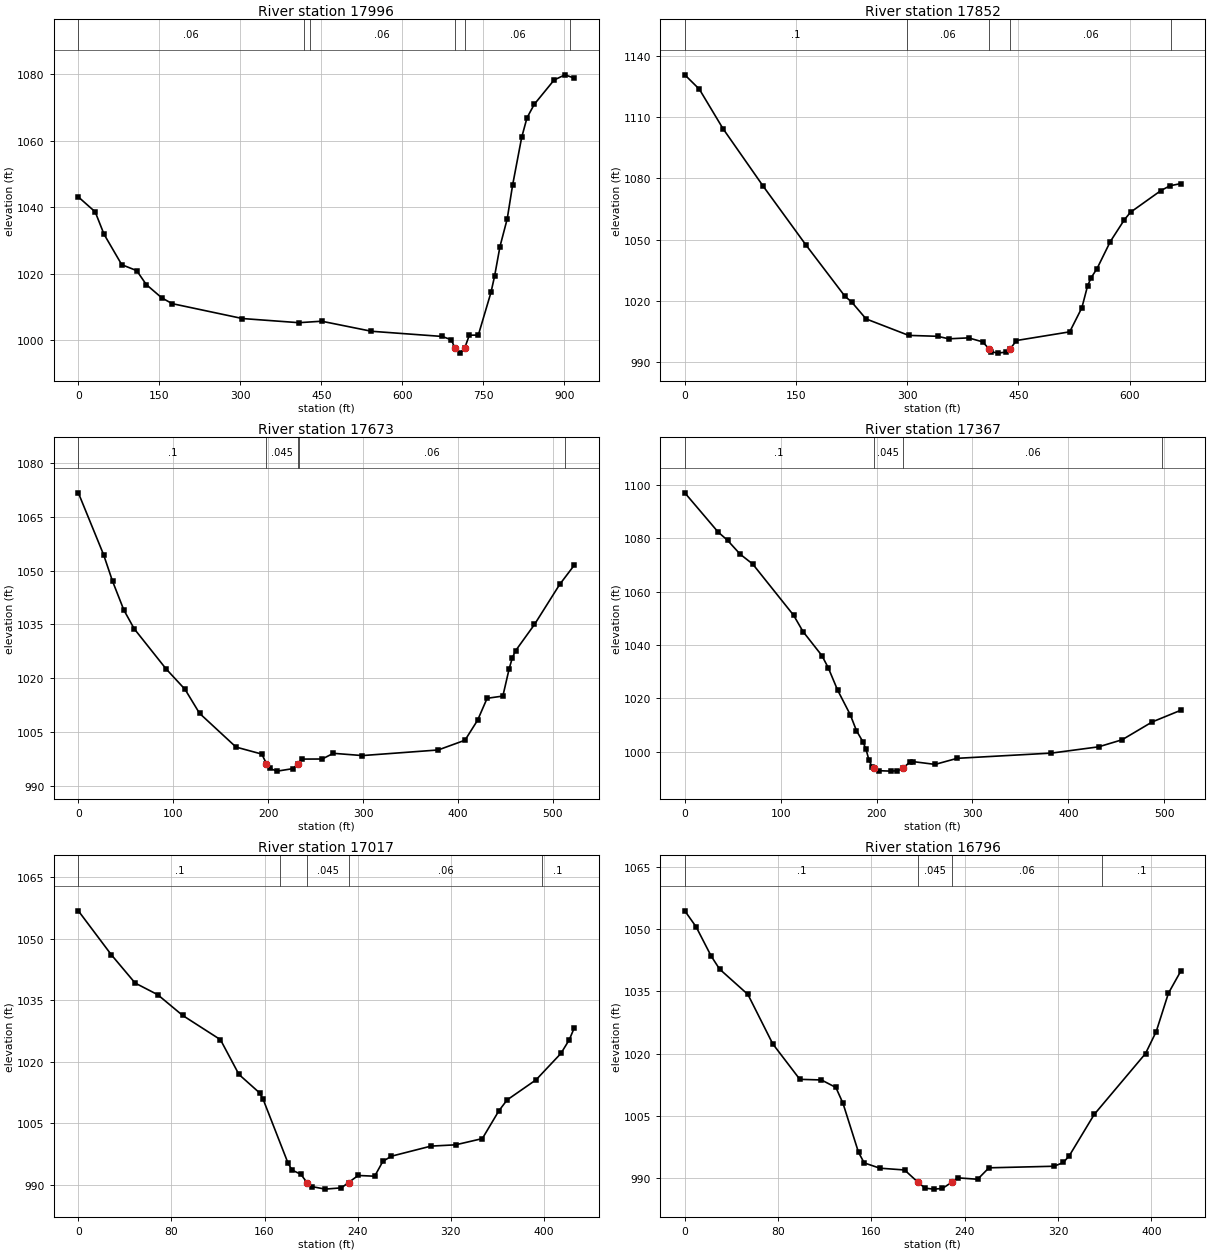
Type RM Length L Ch R = 1 ,17996   ,148.8,144.3,139.4
XS GIS Cut Line= 6
1682129.16766959 468181.662509421681750.29907287468029.313319141
1681579.82338792468055.3591345851681506.18606801468069.590077251
1681408.00253734468088.564448759 1681248.4546281468119.398376584
#Sta/Elev= 30
       0 1043.09    31.2  1038.6    47.6 1031.87    80.4 1022.72   108.1 1020.94
   125.8 1016.76   154.4 1012.77   173.7 1011.02   303.8 1006.54   408.4 1005.29
   450.7 1005.73   542.9 1002.71     674 1001.15   690.7 1000.14697.3192997.7176
   707.4  996.14715.6392997.6802   724.1 1001.53   740.8 1001.56   764.2 1014.37
   770.9 1019.26   780.9 1028.18   794.3 1036.48   804.3 1046.64   821.1 1060.99
     831 1066.89   844.4 1070.92   881.1 1078.22   901.2 1079.79   918.3 1078.82
#Mann= 6 ,-1,0
       0     .06       0  418.35      .1       0  428.35     .06       0
697.3192    .045       0715.6392     .06       0  910.81      .1       0
Bank Sta=697.3192,715.6392
XS Rating Curve= 0 ,0
Exp/Cntr(USF)=0,0
Exp/Cntr=0.3,0.1

Type RM Length L Ch R = 1 ,17852   ,180,178.6,176.5
XS GIS Cut Line= 4
1681744.63511025467671.0454478331681522.46174048467880.189360488
1681340.80778762467986.8123328231681248.99356144 468109.23130106
#Sta/Elev= 30
       0 1130.63    19.6 1123.61    51.5 1104.33   105.7 1076.19   163.1 1047.58
   215.8 1022.45   225.4 1019.41   244.5 1011.28     302 1003.22   340.9 1002.78
   356.1 1001.55   382.7 1002.01   401.7 1000.07 409.972996.8022   413.2  995.29
   421.9  994.55   433.9  995.08 439.272996.7856   447.4 1000.72   519.2 1004.96
   535.6 1016.74   543.2 1027.32   547.9 1031.31   556.1 1035.92     574 1049.13
     593 1059.81   601.2 1063.43   642.2 1074.03   654.5 1076.39   668.8 1077.42
#Mann= 5 ,-1,0
       0      .1       0     300     .06       0 409.972    .045       0
 439.272     .06       0  655.76      .1       0
Bank Sta=409.972,439.272
XS Rating Curve= 0 ,0
Exp/Cntr(USF)=0,0
Exp/Cntr=0.3,0.1

Type RM Length L Ch R = 1 ,17673   ,319.6,306,289.9
XS GIS Cut Line= 5
1681507.70874801467660.1657436361681436.45331309467710.948122384
1681375.37699167467754.4762505461681181.57783619467896.448053596
1681201.30082972468014.405106268
#Sta/Elev= 30
       0 1071.71    26.6 1054.46      36 1047.08    47.9 1039.04    58.8  1033.8
    92.4  1022.6   112.4 1016.88   127.7 1010.19   166.1 1000.78   193.3  998.82
 198.077996.1742   201.4  994.82   209.5  994.07   226.4  994.78231.0941996.1176
   235.8  997.43   256.9  997.45   268.6  999.04   299.2  998.41     379  999.97
   407.3 1002.69   420.6 1008.28   430.6 1014.39   447.2 1015.01   453.9  1022.7
   457.2  1025.7   460.6 1027.66   480.5 1034.98   507.1 1046.17   522.3 1051.48
#Mann= 5 ,-1,0
       0      .1       0 198.077    .045       0231.0941      .1       0
   232.5     .06       0  512.74      .1       0
Bank Sta=198.077,231.0941
XS Rating Curve= 0 ,0
Exp/Cntr(USF)=0,0
Exp/Cntr=0.3,0.1

Type RM Length L Ch R = 1 ,17367   ,341.5,349.6,355.1
XS GIS Cut Line= 6
 1681091.7541036467446.3006414181681089.95751926467533.780781418
1681089.01362352467608.7553690081681087.90010868 467708.75057584
1681087.18915211467783.7845465091681086.38131869467963.487704513
#Sta/Elev= 30
       0 1097.05    34.7 1082.37    44.6 1079.25    57.7 1074.06    70.8 1070.37
   113.5 1051.16   123.3 1045.05     143 1036.04   149.6 1031.51   159.4 1023.09
   172.6 1013.88   179.1 1007.87   185.7 1003.78     189 1000.96   192.2  996.73
   195.5  994.29   196.9993.8964   202.1  992.89   215.2  992.73   221.8  992.88
  227.61993.8969   234.9  996.13   238.2  996.29   261.1  995.25   284.1  997.53
   382.5  999.49   431.7 1001.84   456.2 1004.49   487.5 1011.16   517.2 1015.52
#Mann= 4 ,-1,0
       0      .1       0   196.9    .045       0  227.61     .06       0
  497.52      .1       0
Bank Sta=196.9,227.61
XS Rating Curve= 0 ,0
Exp/Cntr(USF)=0,0
Exp/Cntr=0.3,0.1

Type RM Length L Ch R = 1 ,17017   ,219.9,221.5,222.7
XS GIS Cut Line= 6
 1680814.6417447467420.8099213841680791.82781395467506.110603794
1680767.89380669467577.394910052 1680729.3249862 467669.65784888
1680700.39820678467738.8548889611680666.65024279467819.584714383
#Sta/Elev= 30
       0 1056.78    28.4 1046.05    48.8 1039.17    68.2 1036.33    89.5  1031.3
   122.1 1025.36     138 1016.88   155.8 1012.37   158.8  1010.8     180  995.38
   183.5  993.58   191.2  992.54  196.39990.5289   200.9  989.53     212  988.92
     226  989.23  232.14990.5297   240.4  992.25   254.6  992.07   261.7  995.71
     269  996.95     303  999.41   324.1  999.72   347.1 1001.24   361.3 1008.01
   368.4 1010.67   393.3 1015.58   414.6    1022   421.8 1025.34     426 1028.17
#Mann= 5 ,-1,0
       0      .1       0  173.49     .06       0  196.39    .045       0
  232.14     .06       0  398.49      .1       0
Bank Sta=196.39,232.14
XS Rating Curve= 0 ,0
Exp/Cntr(USF)=0,0
Exp/Cntr=0.3,0.1

Type RM Length L Ch R = 1 ,16796   ,299.9,300,300
XS GIS Cut Line= 6
1680647.37741818 467341.231625841680606.74856243467418.726877674
1680571.92382893467485.1516135931680525.49085093467573.718037501
1680490.66611743467640.1424453411680450.03726168467717.638025254
#Sta/Elev= 30
       0 1054.42     9.7 1050.56    22.6 1043.51    29.8 1040.37    54.1 1034.25
    75.4 1022.33    98.6 1013.78   117.1 1013.63   129.5 1011.82   135.6 1007.99
   148.9  996.17   153.8  993.62   167.2  992.35   188.4  991.92  199.73 988.991
     206  987.53   213.4   987.3   220.8  987.46  229.05988.9939     234  990.02
     251  989.68   260.7  992.44   316.6  992.82   324.6  993.74   329.7  995.41
   350.9  1005.3   394.9    1020   404.1 1025.31   414.5 1034.52     425 1039.81
#Mann= 4 ,-1,0
       0      .1       0  199.73    .045       0  229.05     .06       0
   357.5      .1       0
Bank Sta=199.73,229.05
XS Rating Curve= 0 ,0
Exp/Cntr(USF)=0,0
Exp/Cntr=0.3,0.1

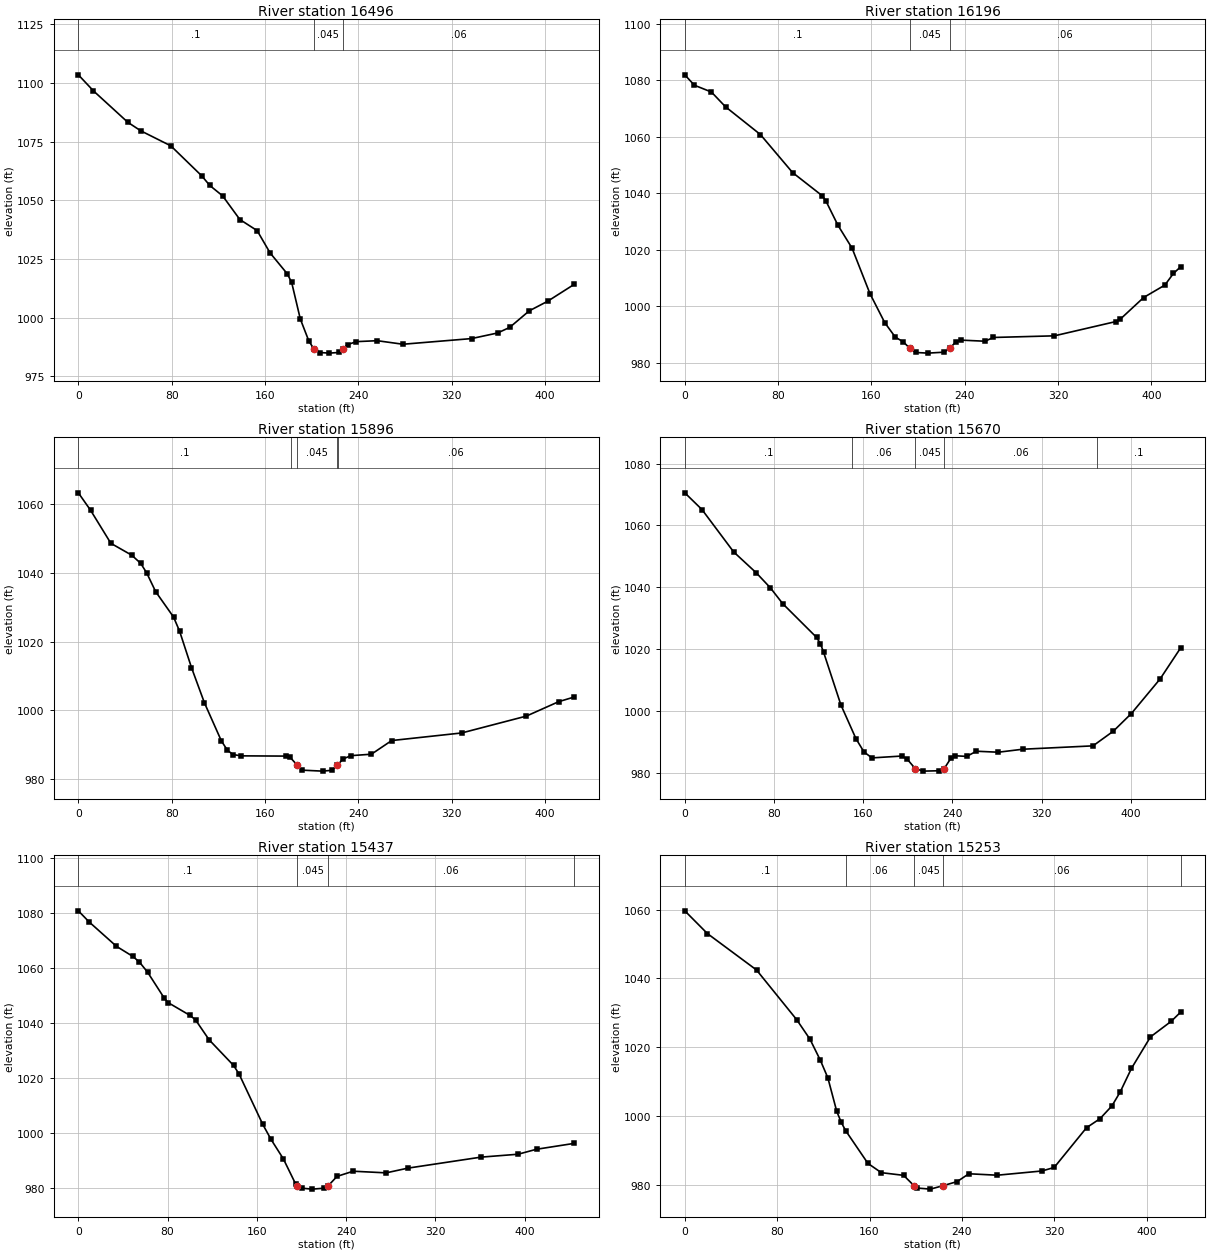
Type RM Length L Ch R = 1 ,16496   ,299.9,300,298.1
XS GIS Cut Line= 6
  1680385.601695467194.1144660121680345.23333742467271.745872423
1680310.63170059467338.2870779191680264.49629417467427.008685261
1680231.40744959467494.3363065121680194.90981917467573.980832249
#Sta/Elev= 30
       0 1103.39      13 1096.54    42.4  1083.2    53.5 1079.57    79.3 1073.16
   105.8 1060.39   112.7  1056.3   123.7 1051.87   138.5 1041.79   153.3 1037.08
   164.4 1027.59   179.2 1018.65   182.9 1015.02   190.3  999.48   197.7     990
  201.95986.7562   207.6  985.18   214.9  984.93   223.6  985.21  226.55986.7543
     231  988.56   238.3  989.82   256.3  990.22   278.3  988.71   337.1  991.12
   359.4   993.5   369.8  995.87   386.6 1002.93   402.3 1006.99   425.1 1014.19
#Mann= 3 ,-1,0
       0      .1       0  201.95    .045       0  226.55     .06       0
Bank Sta=201.95,226.55
XS Rating Curve= 0 ,0
Exp/Cntr(USF)=0,0
Exp/Cntr=0.3,0.1

Type RM Length L Ch R = 1 ,16196   ,300.5,300,300.1
XS GIS Cut Line= 6
1680073.39825118467108.6408836691680042.80874543467190.619722337
1680016.58930968467260.8872983461679981.63006201467354.577399671
1679955.41062626467424.8453037591679924.82144859467506.824142426
#Sta/Elev= 30
       0 1081.95     8.2 1078.27    22.8 1075.87    34.9 1070.64    64.8 1060.82
    92.4 1047.36   117.9 1039.13   120.8 1037.44   131.3 1028.69   143.4 1020.59
   158.7 1004.53   171.4  994.25   180.4  989.15   187.4  987.41   192.9985.1611
   197.9   983.7   208.4  983.47   222.4  983.81  226.92985.1617   232.6  987.53
   236.4  988.08   257.4  987.68   264.4  989.01   316.8  989.59   369.5  994.64
     373  995.38   393.3 1003.15   411.5 1007.55   418.8 1011.65     425 1014.03
#Mann= 3 ,-1,0
       0      .1       0   192.9    .045       0  226.92     .06       0
Bank Sta=192.9,226.92
XS Rating Curve= 0 ,0
Exp/Cntr(USF)=0,0
Exp/Cntr=0.3,0.1

Type RM Length L Ch R = 1 ,15896   ,224.4,226.1,226.3
XS GIS Cut Line= 6
1679795.01101267466992.2018120881679765.26107217467074.488720998
1679739.76112318467145.020732179 1679705.7608631467239.063195005
1679680.26058601467309.5952061711679650.51097359467391.882443175
#Sta/Elev= 30
       0 1063.32    10.5 1058.24    27.9 1048.61    45.8 1045.15    53.5 1042.76
    58.6 1039.98    66.3 1034.52    81.6 1027.14    86.8 1023.01      97  1012.4
   108.1 1002.13   122.6  991.05   127.8  988.31   132.6  987.07   139.5  986.69
   177.9  986.62   181.6  986.23  187.63983.9783     192  982.52   209.3  982.24
   217.4  982.48  222.13983.9755   226.8  985.77   233.7  986.75   251.2  987.17
   268.6  991.15   328.6  993.36     384  998.27   411.7 1002.47     425 1003.83
#Mann= 5 ,-1,0
       0      .1       0   182.5     .06       0  187.63    .045       0
  222.13      .1       0   222.5     .06       0
Bank Sta=187.63,222.13
XS Rating Curve= 0 ,0
Exp/Cntr(USF)=0,0
Exp/Cntr=0.3,0.1

Type RM Length L Ch R = 1 ,15670   ,230.1,232.3,231.8
XS GIS Cut Line= 2
1679605.58324192466886.0635729281679437.57164513467297.895219623
#Sta/Elev= 30
       0 1070.56    15.4 1065.15    43.8 1051.45    64.1 1044.67    76.7 1039.84
    87.9 1034.66   118.2 1023.77   121.7 1021.71   124.5 1018.98     140 1001.95
   153.6  990.94   160.7  986.72   167.8  984.76     195  985.37   199.7  984.28
  206.65981.3132   213.8  980.48     228   980.6   232.7  981.29   238.6   984.6
   242.2  985.46   252.9  985.25   261.6  986.92   281.2   986.6   303.2  987.57
   366.2  988.66   384.4   993.4   400.6  999.12   426.4 1010.32   444.8 1020.36
#Mann= 5 ,-1,0
       0      .1       0     150     .06       0  206.65    .045       0
   232.7     .06       0     370      .1       0
Bank Sta=206.65,232.7
XS Rating Curve= 0 ,0
Exp/Cntr(USF)=0,0
Exp/Cntr=0.3,0.1

Type RM Length L Ch R = 1 ,15437   ,183.6,184.8,185.7
XS GIS Cut Line= 3
1679438.37753122466759.660901222 1679289.3028199467051.886825401
1679269.55782503467166.407795687
#Sta/Elev= 30
       0 1080.73     9.8 1076.65    34.2 1067.82    48.9 1064.15    54.8 1062.09
    62.2 1058.35    76.9 1049.07    80.6 1047.34   100.1 1042.72     105 1041.11
   117.2 1033.86   139.1 1024.55     144 1021.46   165.3  1003.1   172.7  997.65
   183.7  990.61   194.8   981.4   196.1   980.8   200.1  979.95   209.5   979.6
   220.5  979.94  223.87980.8034   231.8  984.23   246.3  986.11   275.8  985.51
   295.2  987.22   360.7  991.22     394  992.28   410.6  994.09   444.3  996.22
#Mann= 4 ,-1,0
       0      .1       0   196.1    .045       0  223.87     .06       0
  444.26      .1       0
Bank Sta=196.1,223.87
XS Rating Curve= 0 ,0
Exp/Cntr(USF)=0,0
Exp/Cntr=0.3,0.1

Type RM Length L Ch R = 1 ,15253   ,254,256.8,258.7
XS GIS Cut Line= 2
1679290.83923147 466683.530628171679064.37426576467048.318904223
#Sta/Elev= 30
       0 1059.64    19.6 1053.03    62.1 1042.47    96.9 1028.04   108.4 1022.37
   117.4 1016.25   123.9 1011.14   131.6  1001.4   135.5  998.22   139.3  995.82
   158.6  986.31   170.2  983.62   189.5  982.84   198.4  979.87   201.1  979.16
   212.7  978.84  223.85979.8593   235.9  981.03     246   983.3   270.6  982.88
   309.3  984.11   319.9  985.13   347.9  996.67   359.5  999.27   369.9    1003
   377.1 1007.07   386.8 1013.88   403.3 1023.04   421.2 1027.55   429.4 1030.22
#Mann= 5 ,-1,0
       0      .1       0     140     .06       0   198.4    .045       0
  223.85     .06       0  429.37      .1       0
Bank Sta=198.4,223.85
XS Rating Curve= 0 ,0
Exp/Cntr(USF)=0,0
Exp/Cntr=0.3,0.1