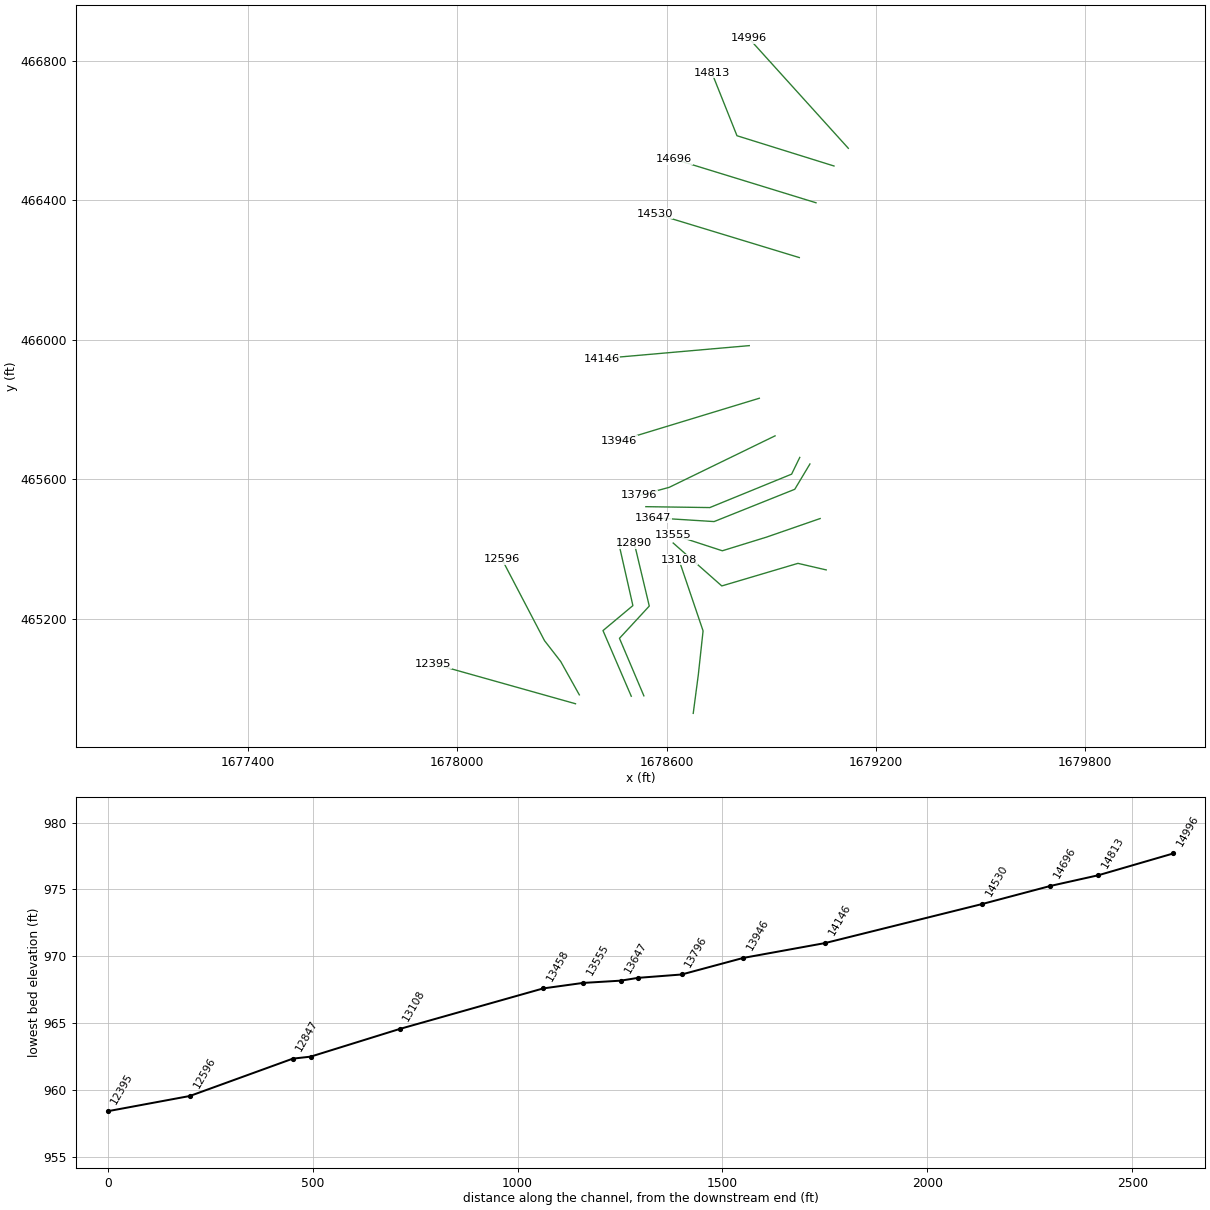
HEC-RAS study HrtRn.prj: HrtRn

--- HrtRn.g01 (geometry) --- (continued)

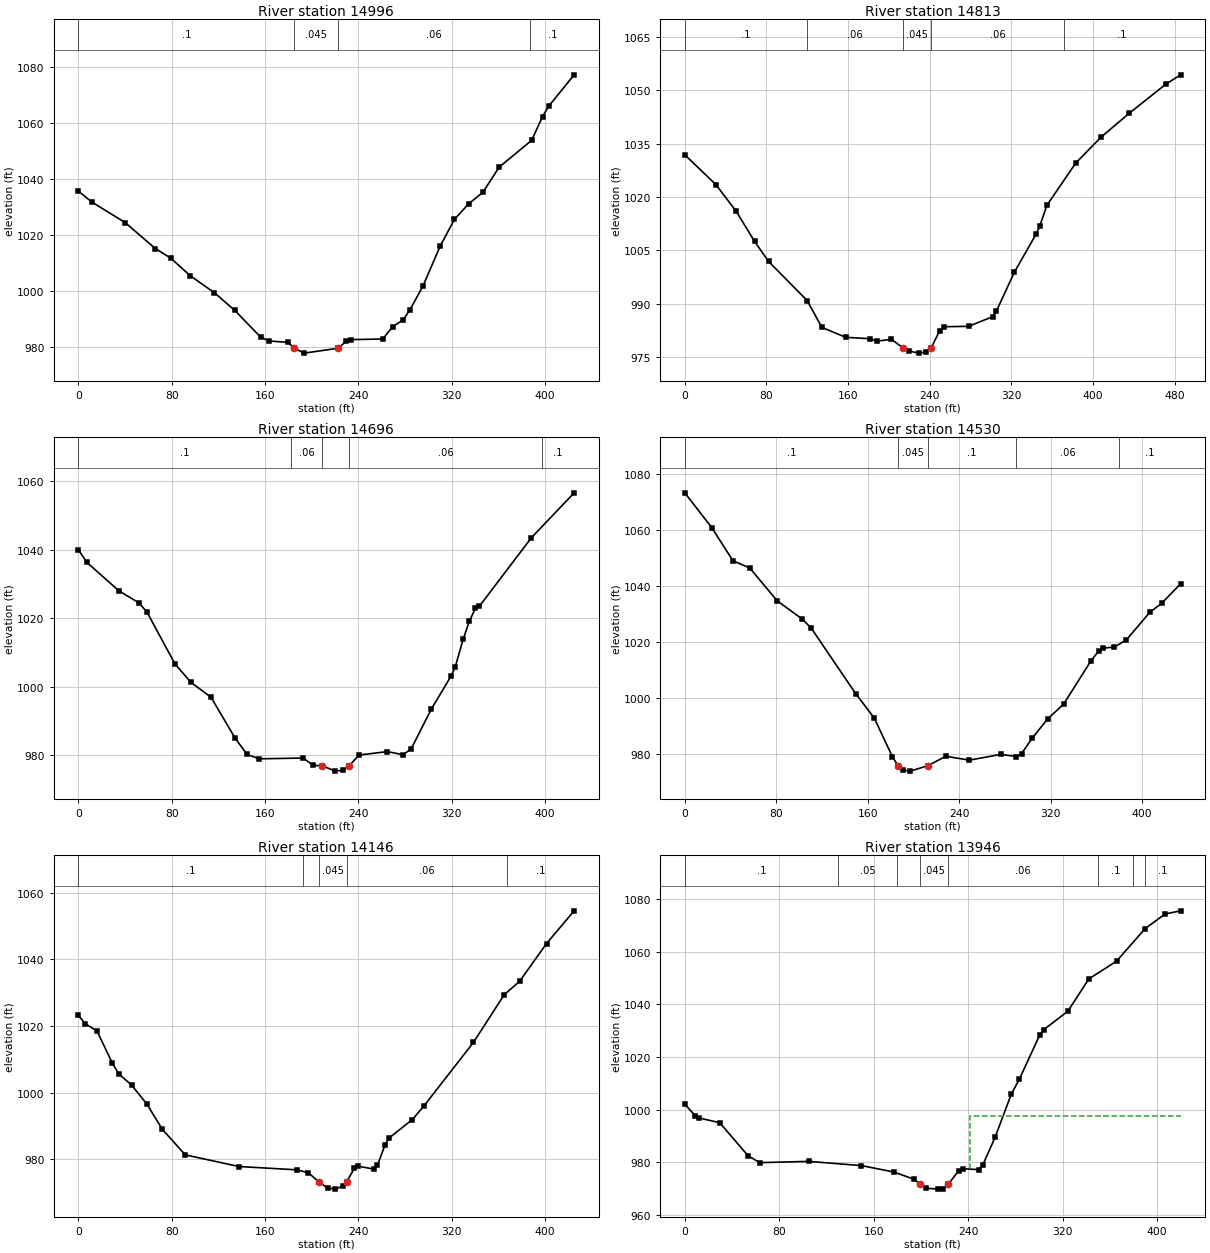
Type RM Length L Ch R = 1 ,14996   ,174.1,183,189.6
XS GIS Cut Line= 6
1679120.85881767 466549.541608171679062.19915809466614.466675177
  1679011.919403466670.1171544191678944.88016701466744.317793429
1678894.60041192466799.9682726711678835.94075234466864.893339679
#Sta/Elev= 30
       0 1035.54    11.6 1031.62    40.2 1024.27      66 1015.02    79.3 1011.58
    95.9 1005.31   116.6  999.27     134  992.98   156.3  983.39   163.3  982.04
   179.6  981.53   185.2979.4267   193.5  977.69   222.7979.4237   229.6  981.93
     234  982.52   260.9  982.72   269.4  987.15   278.2  989.46   284.1  993.05
   295.5 1001.73   310.2 1015.93   322.4 1025.45   334.6    1031   346.8 1035.11
   360.7 1044.06   388.5 1053.63   397.9  1062.1   403.1 1065.79     425 1077.03
#Mann= 4 ,-1,0
       0      .1       0   185.2    .045       0   222.7     .06       0
   387.5      .1       0
Bank Sta=185.2,222.7
XS Rating Curve= 0 ,0
Exp/Cntr(USF)=0,0
Exp/Cntr=0.3,0.1

Type RM Length L Ch R = 1 ,14813   ,117.7,117,117.3
XS GIS Cut Line= 3
1679079.84106718466498.7426381891678801.73054145466585.551019461
1678729.68629597 466766.15508691
#Sta/Elev= 30
       0  1031.9    30.5 1023.48    50.5 1015.93    68.3 1007.53    82.1 1001.86
   119.9  990.85   134.3   983.3   157.7  980.51   181.5  980.12   188.6  979.45
   202.4  979.94   213.7  977.58   219.5  976.64   229.8  976.06   236.5  976.42
  241.55   977.6   249.6  982.32   253.9  983.49     278   983.6   301.8  986.33
   305.3  987.89   322.9  998.85   344.1 1009.51   347.7 1011.75   354.7 1017.62
     383 1029.56   407.7 1036.82   435.4 1043.56   471.3 1051.77   485.8  1054.4
#Mann= 5 ,-1,0
       0      .1       0     120     .06       0   213.7    .045       0
  241.55     .06       0  371.34      .1       0
Bank Sta=213.7,241.55
XS Rating Curve= 0 ,0
Exp/Cntr(USF)=0,0
Exp/Cntr=0.3,0.1

Type RM Length L Ch R = 1 ,14696   ,167.6,166.3,167
XS GIS Cut Line= 6
1679028.19594526466393.305700168  1678944.565207466419.037932172
1678872.88162334466441.094318509 1678777.3037305466470.502396166
1678705.62014684466492.558782503 1678621.9894086466518.291014507
#Sta/Elev= 30
       0 1040.03     7.3 1036.32    34.8 1027.99      52 1024.46    58.8  1021.8
    82.8 1006.64    96.6  1001.2   113.7  996.88   134.3  984.96   144.6  980.16
   154.9  978.86   192.7  979.09   201.3  976.94   209.2  976.83   220.1  975.26
     227  975.53  232.19976.8369   240.7  979.97   264.8  980.97   278.5  980.06
   285.4  981.85   302.5  993.36   319.7 1003.19   323.1 1005.78     330 1013.97
   335.1 1019.03   340.3 1022.85   343.7 1023.44   388.3 1043.51     425 1056.66
#Mann= 5 ,-1,0
       0      .1       0   182.5     .06       0   209.2    .045       0
  232.19     .06       0   397.5      .1       0
Bank Sta=209.2,232.19
XS Rating Curve= 0 ,0
Exp/Cntr(USF)=0,0
Exp/Cntr=0.3,0.1

Type RM Length L Ch R = 1 ,14530   ,379.2,383.5,387.9
XS GIS Cut Line= 2
1678980.38160942466236.1127018161678565.58354402466362.406676098
#Sta/Elev= 30
       0 1073.28    23.7  1060.8    42.1 1049.01    56.8 1046.44    80.8 1034.72
   102.6 1028.23   110.5 1025.02   149.4  1001.6   165.7  992.86   181.5  979.08
  186.41975.8807   190.5  974.28   197.2  973.91  212.69975.8807   228.3  979.22
   248.8  977.83   276.3  979.88     290  979.13   294.5  980.19   303.7  985.61
   317.4  992.61   331.2  997.77   355.2 1013.29     362 1016.84   365.4 1017.77
   375.7 1018.25     386  1020.7   406.6  1030.6   416.9 1033.79   433.6 1040.79
#Mann= 5 ,-1,0
       0      .1       0  186.41    .045       0  212.69      .1       0
     290     .06       0     380      .1       0
Bank Sta=186.41,212.69
XS Rating Curve= 0 ,0
Exp/Cntr(USF)=0,0
Exp/Cntr=0.3,0.1

Type RM Length L Ch R = 1 ,14146   ,197.1,199.6,202.1
XS GIS Cut Line= 6
1678836.97060592465983.5156093611678749.78672518465975.911950029
1678675.07493234465969.3433936011678575.45931792465960.585865192
 1678500.7475251465954.0176368581678413.59284376 465946.41693028
#Sta/Elev= 30
       0 1023.17     6.1 1020.65      16  1018.5    29.1 1008.88    34.5 1005.67
    45.6 1002.27    58.8  996.53      72  988.95    91.7  981.28   137.8  977.78
   187.2  976.79   197.1  975.92  205.91973.2639   213.6  971.33   220.2  970.99
   226.7  971.88  230.05973.2621   236.6  977.21   239.9  977.88   253.1  977.02
   256.4   978.2     263  984.37   266.3  986.33   286.3   991.9   295.9  995.83
   338.7 1015.09   365.1 1029.44   378.2 1033.41   401.3 1044.78     425 1054.61
#Mann= 5 ,-1,0
       0      .1       0  192.51     .06       0  205.91    .045       0
  230.05     .06       0  367.51      .1       0
Bank Sta=205.91,230.05
XS Rating Curve= 0 ,0
Exp/Cntr(USF)=0,0
Exp/Cntr=0.3,0.1

Type RM Length L Ch R = 1 ,13946   ,148.6,150.5,152.7
XS GIS Cut Line= 2
1678865.77267979465832.6333917511678463.96203405465710.214423514
#Sta/Elev= 30
       0 1002.12       9  997.67    12.4  996.83    29.6  995.08    53.6  982.53
    63.6  979.93     105   980.4   149.6  978.81   177.1  976.38   194.2  973.63
  199.47 971.652   204.5  970.24   214.8  969.88   218.7   970.1  223.14971.6523
   231.9  976.86   235.4  977.62   249.1  977.28   252.5  979.09   262.8   989.5
   276.5 1005.85   283.4 1011.62   300.5  1028.2     304 1030.36   324.5 1037.39
   342.2 1049.61   365.7 1056.36     390 1068.76   406.9 1074.28     420 1075.47
#Mann= 8 ,-1,0
       0      .1       0     130     .05       0     180     .06       0
  199.47    .045       0  223.14     .06       0     350      .1       0
     380     .06       0     390      .1       0
#XS Ineff= 2 , 0
                          241.66          997.61
Permanent Ineff=
       F       F
Bank Sta=199.47,223.14
XS Rating Curve= 0 ,0
Exp/Cntr(USF)=0,0
Exp/Cntr=0.3,0.1

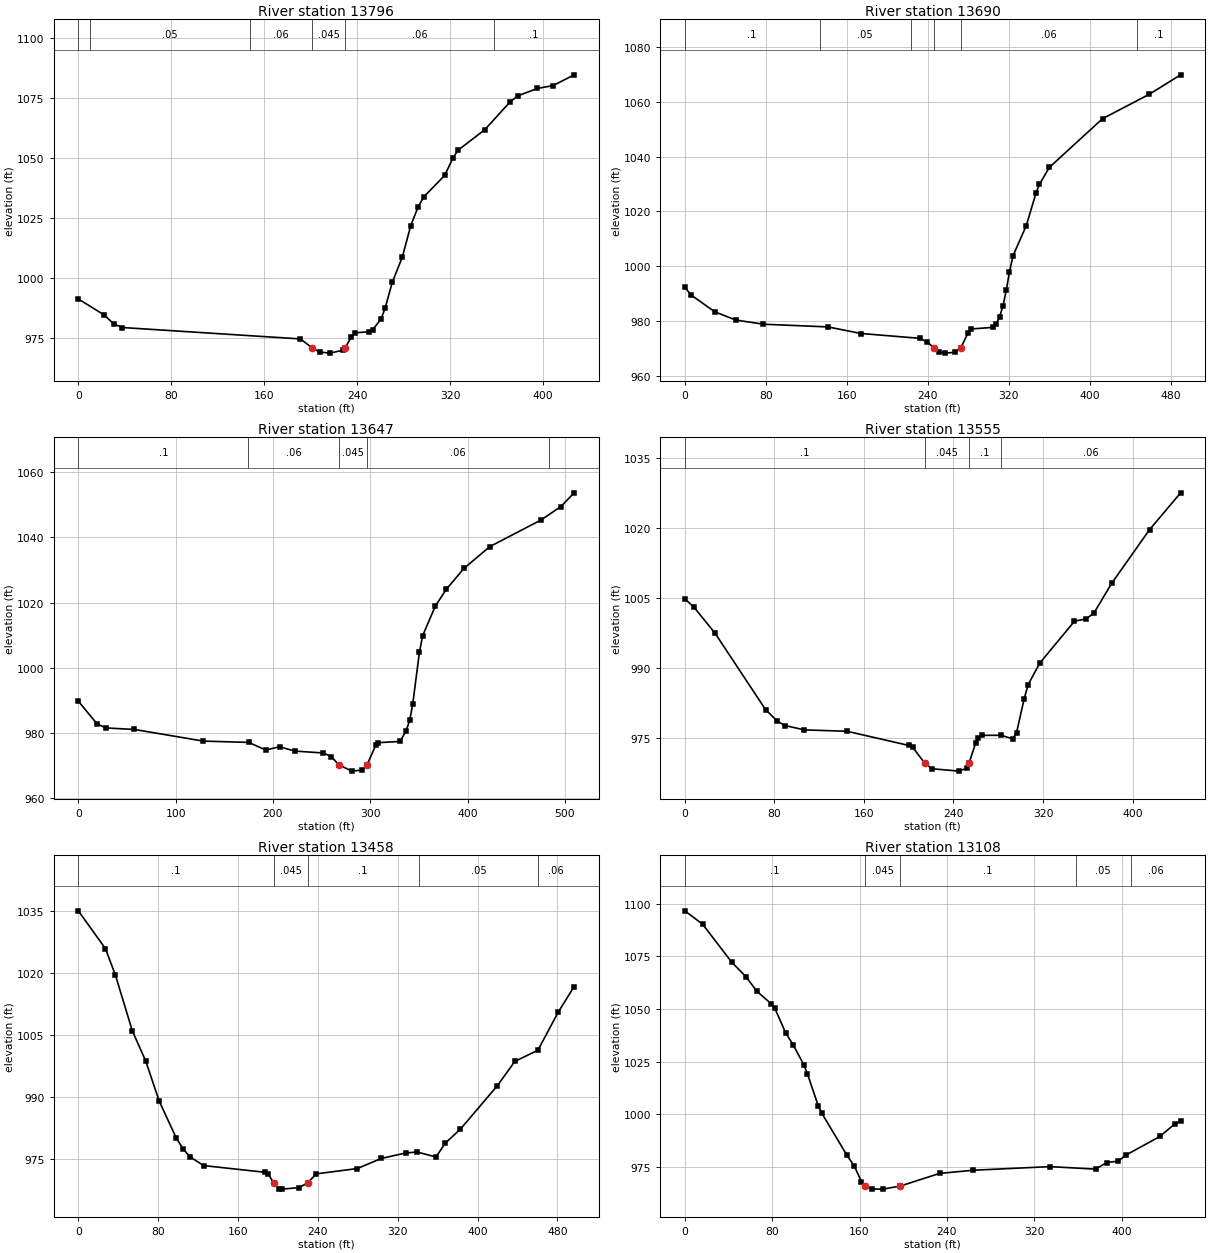
Type RM Length L Ch R = 1 ,13796   ,107.1,106.1,105.5
XS GIS Cut Line= 6
1678910.91533992465724.7781658321678832.23964426 465686.48460725
1678764.80342743465653.6618382481678674.88858101465609.897818178
1678607.45236418465577.0747210831678521.51651242465553.697143167
#Sta/Elev= 30
       0  991.25    22.3  984.56    30.6  980.76    37.9  979.33   191.1  974.57
  201.07970.8618   207.5  969.11   216.7  968.64   227.6  969.86  229.63970.8611
   234.9  975.41   238.2   977.1   250.5  977.58   253.2  978.41   260.5  982.89
   264.1  987.62   270.1  998.21   278.7 1008.66     286 1021.86   292.2 1029.52
   297.1 1033.81   315.2 1042.84   322.5 1050.27   326.6 1053.31   349.7 1061.92
   371.2 1073.37   377.9    1076   394.9 1079.13   408.5 1080.33   426.6 1084.82
#Mann= 6 ,-1,0
       0      .1       0      10     .05       0   147.5     .06       0
  201.07    .045       0  229.63     .06       0   357.5      .1       0
Bank Sta=201.07,229.63
XS Rating Curve= 0 ,0
Exp/Cntr(USF)=0,0
Exp/Cntr=0.3,0.1

Type RM Length L Ch R = 1 ,13690   ,42.3,42.3,42.1
XS GIS Cut Line= 4
1678981.65931265465662.855855852 1678958.3408686465614.923498639
1678723.86095899465519.0587842121678540.55207938465521.649722439
#Sta/Elev= 30
       0  992.36     6.6  989.47    29.6  983.45    50.4  980.44    77.6  978.93
   141.4  977.94   174.2  975.54     232  973.79   239.6  972.47   246.2970.3132
   251.2  968.84   257.2  968.39   267.3   968.7  272.75 970.315   279.8  975.62
   283.1  977.19   304.4  977.77   307.8  979.02   311.1  981.65   314.4  985.53
   317.8  991.49   320.8   997.9   324.4 1003.91   337.4 1014.78   347.2 1026.85
   350.5 1029.91   360.3 1036.08   412.8  1053.8   458.8 1062.65     490 1069.79
#Mann= 6 ,-1,0
       0      .1       0   133.3     .05       0   223.3     .06       0
   246.2    .045       0  272.75     .06       0  446.62      .1       0
Bank Sta=246.2,272.75
XS Rating Curve= 0 ,0
Exp/Cntr(USF)=0,0
Exp/Cntr=0.3,0.1

Type RM Length L Ch R = 1 ,13647   ,93.3,92.2,90.1
XS GIS Cut Line= 4
1679010.80736771465644.071553701 1678967.4091524465571.525283324
1678736.16791557465478.8992416821678560.63185064 465489.91072915
#Sta/Elev= 30
       0  989.68    19.4  982.65    28.5  981.45    57.7  980.98   128.4  977.41
     175  977.01   192.7  974.66   206.8  975.68   222.3  974.34   251.9  973.76
   259.9  972.64  267.82970.1021   281.1  968.18   291.7   968.5  296.67970.1004
   305.8  976.26   308.1  976.93   330.5   977.3   336.7  980.46   340.6  983.89
   343.7  988.95   350.5 1004.74   353.8  1009.8   366.9 1018.93   378.1 1024.06
   396.3  1030.5   422.8 1037.18   475.4 1045.35   495.7 1049.46   509.5 1053.71
#Mann= 5 ,-1,0
       0      .1       0  174.54     .06       0  267.82    .045       0
  296.67     .06       0  483.64      .1       0
Bank Sta=267.82,296.67
XS Rating Curve= 0 ,0
Exp/Cntr(USF)=0,0
Exp/Cntr=0.3,0.1

Type RM Length L Ch R = 1 ,13555   ,97.3,97.1,97.2
XS GIS Cut Line= 5
1679040.09812219465487.597274681 1678957.4250592465458.937555109
1678886.56201194465434.3719874371678759.69154917465395.140770368
1678619.42482323465441.057993219
#Sta/Elev= 30
       0 1004.79     8.1 1003.06      27  997.48    72.1  981.17    82.5   978.7
    89.5  977.75   106.8  976.82     145  976.52   200.2  973.49   203.6  973.08
  214.23969.7543   220.8  968.52   244.8  968.01   251.7  968.62  253.96 969.754
   259.9  974.08     262  975.18   265.1  975.64   282.6  975.67   292.9   974.9
   296.3   976.2   303.2  983.52   306.7  986.48     317  991.06   348.1 1000.04
   358.4 1000.53   365.4 1001.76   381.3 1008.12   415.1 1019.58   442.9 1027.46
#Mann= 4 ,-1,0
       0      .1       0  214.23    .045       0  253.96      .1       0
   282.5     .06       0
Bank Sta=214.23,253.96
XS Rating Curve= 0 ,0
Exp/Cntr(USF)=0,0
Exp/Cntr=0.3,0.1

Type RM Length L Ch R = 1 ,13458   ,369.5,350.1,301.7
XS GIS Cut Line= 4
1679057.44425581465340.284046497 1678976.4774362465359.068348648
1678758.19089051465294.2948929541678618.92796077465417.364458773
#Sta/Elev= 30
       0 1035.05    27.1 1025.91    37.2 1019.44    54.1 1005.95    67.5  998.66
      81  988.94    98.1  979.99   104.9  977.37   111.8  975.43   125.5  973.31
   187.1  971.68   190.5  971.15  195.56969.1757   200.7  967.72   204.2   967.6
   221.3  967.97  229.93969.1782   238.4   971.3   279.5  972.59   303.4  975.03
   327.9  976.36   339.5  976.59   358.3  975.38   367.4  978.69   382.8  982.15
   419.6  992.62   437.3  998.55   460.4 1001.27   480.8 1010.53   496.7 1016.69
#Mann= 5 ,-1,0
       0      .1       0  195.56    .045       0  229.93      .1       0
  340.81     .05       0  460.81     .06       0
Bank Sta=195.56,229.93
XS Rating Curve= 0 ,0
Exp/Cntr(USF)=0,0
Exp/Cntr=0.3,0.1

Type RM Length L Ch R = 1 ,13108   ,222.4,217.5,202.2
XS GIS Cut Line= 4
1678676.32957007464928.795883339 1678690.8773926 465039.24450054
1678704.55621309465165.3933561081678635.27476317465369.759784172
#Sta/Elev= 30
       0 1096.64    16.3 1090.31    42.8 1072.36      56 1065.36      66  1058.5
    79.2 1052.48    82.5 1050.34    92.4 1038.71    99.1 1033.16     109 1023.58
   112.3 1019.32   122.2 1004.12   125.5 1000.58   148.6  980.55   155.2  975.55
   161.8  968.15  164.61966.0505   171.7  964.62   181.6  964.57  197.45  966.05
   233.3  972.02   263.7  973.52   334.4  975.25   376.2  974.06   386.5   977.2
   396.9  977.85   403.9  980.69   435.1  989.57   448.6  995.45   454.1  996.93
#Mann= 5 ,-1,0
       0      .1       0  164.61    .045       0  197.45      .1       0
  358.29     .05       0  408.29     .06       0
Bank Sta=164.61,197.45
XS Rating Curve= 0 ,0
Exp/Cntr(USF)=0,0
Exp/Cntr=0.3,0.1

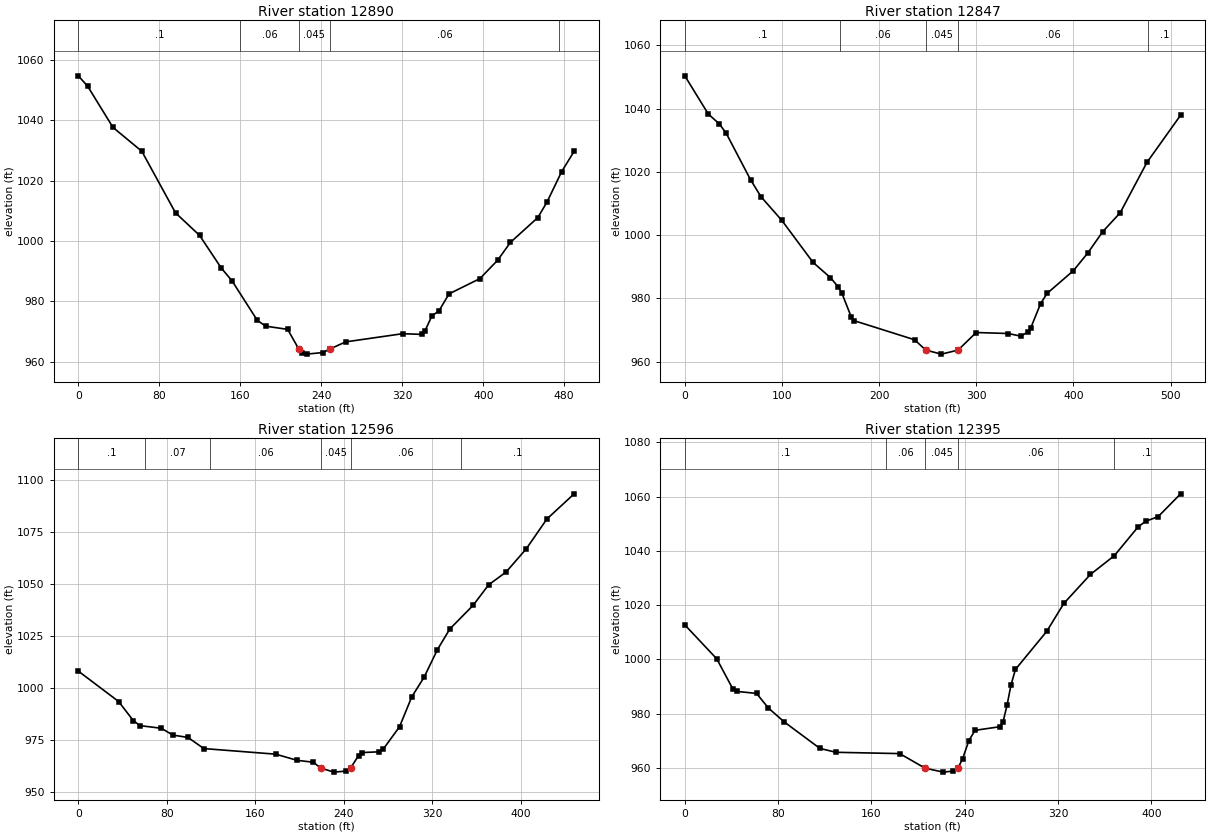
Type RM Length L Ch R = 1 ,12890   ,45.8,43.5,41.1
XS GIS Cut Line= 5
1678534.87174479464979.0863356981678464.91641264465144.064327349
1678529.62509488465214.0196594971678550.35135676465236.592098151
1678507.57670813465416.198761606
#Sta/Elev= 30
       0 1054.69     9.3  1051.2    34.2 1037.61    62.7  1029.7      96  1009.3
   119.8 1001.82   141.3  990.97   151.8  986.79   176.8  973.69   185.1  971.76
   206.8   970.7  217.72964.2079   220.8  962.86   225.4   962.5   241.6  963.02
  248.59964.2067     264  966.55   320.4  969.27   339.3  969.04   342.6  970.32
   349.4  975.24   356.1  976.75   366.2  982.46   396.7  987.52   414.2   993.6
   426.9  999.53   453.9 1007.74   462.9 1012.82   477.5 1022.98   489.8 1029.71
#Mann= 5 ,-1,0
       0      .1       0     160     .06       0  217.72    .045       0
  248.59     .06       0  475.14      .1       0
Bank Sta=217.72,248.59
XS Rating Curve= 0 ,0
Exp/Cntr(USF)=0,0
Exp/Cntr=0.3,0.1

Type RM Length L Ch R = 1 ,12847   ,233.7,251.1,275.3
XS GIS Cut Line= 4
1678498.72815651464977.9204134951678417.69656344465166.216849196
1678503.39184532465237.9210646481678460.61035505465426.736398814
#Sta/Elev= 30
       0 1050.34    24.2 1038.25    35.6 1035.13    42.7 1032.13    67.7 1017.47
    78.4 1012.12    99.9 1004.62     132  991.35   149.9  986.53   158.1  983.53
   161.6  981.68   171.3   974.1   174.1  972.94   236.5  966.89  247.96963.6249
   264.1  962.35  281.23 963.626   299.9  969.18   332.9  968.87     346  968.02
   352.8  969.35   356.1  970.65   366.2  978.33   372.9  981.56   399.9  988.72
   414.8  994.34   430.1 1001.06   448.1 1007.05   475.6 1022.95   510.3  1037.9
#Mann= 5 ,-1,0
       0      .1       0     160     .06       0  247.96    .045       0
  281.23     .06       0  476.73      .1       0
Bank Sta=247.96,281.23
XS Rating Curve= 0 ,0
Exp/Cntr(USF)=0,0
Exp/Cntr=0.3,0.1

Type RM Length L Ch R = 1 ,12596   ,187,200.6,209.6
XS GIS Cut Line= 6
1678349.82263009464981.9469743371678296.66558418465077.267321751
1678249.93634692465137.6002063451678203.62541592465226.230606511
1678168.89188959465292.7029145061678128.36966093465370.254268587
#Sta/Elev= 30
       0 1008.13    36.4  993.52    49.6  984.38    55.7  981.92      75  980.64
    85.4  977.38    99.1  976.23   113.4  970.89   178.4  968.19   197.6  965.24
   212.4  964.31  218.82961.5621   230.9  959.56     242  960.06  246.02961.5612
   253.2  967.48   256.5  968.97   271.7  969.33   275.4  970.55   290.2  981.36
   301.3  995.78   312.4 1005.19   324.5 1018.49   335.6 1028.35   356.8 1039.82
   370.7 1049.62   386.4 1055.72   404.8 1066.99   423.4  1081.3     448 1093.38
#Mann= 6 ,-1,0
       0      .1       0      60     .07       0  119.14     .06       0
  218.82    .045       0  246.02     .06       0  345.45      .1       0
Bank Sta=218.82,246.02
XS Rating Curve= 0 ,0
Exp/Cntr(USF)=0,0
Exp/Cntr=0.3,0.1

Type RM Length L Ch R = 1 ,12395   ,185.8,186.4,187.1
XS GIS Cut Line= 6
1678338.90364605464956.4245869291678254.67153105464980.114500172
1678182.47285655465000.4202338381678086.20762913465027.494654752
1678014.00862655465047.8003884171677929.77651155465071.490301674
#Sta/Elev= 30
       0  1012.7    27.4 1000.17      41  989.23    44.4  988.18    61.5  987.43
    71.7  982.02    85.3   976.9   115.8  967.16   129.6  965.73   184.2  965.25
  205.99959.8688   221.6  958.42   230.2  958.81  234.09959.8712   238.2  963.42
   243.5  970.06   248.8  973.83   270.1  975.16   272.8     977   276.2  983.04
   279.6  990.55   283.4  996.27   310.3 1010.35   324.9 1020.61   347.7 1031.29
   368.2 1038.21   388.6 1048.84   395.1 1050.88   405.8 1052.61     425    1061
#Mann= 5 ,-1,0
       0      .1       0   172.5     .06       0  205.99    .045       0
  234.09     .06       0   367.5      .1       0
Bank Sta=205.99,234.09
XS Rating Curve= 0 ,0
Exp/Cntr(USF)=0,0
Exp/Cntr=0.3,0.1