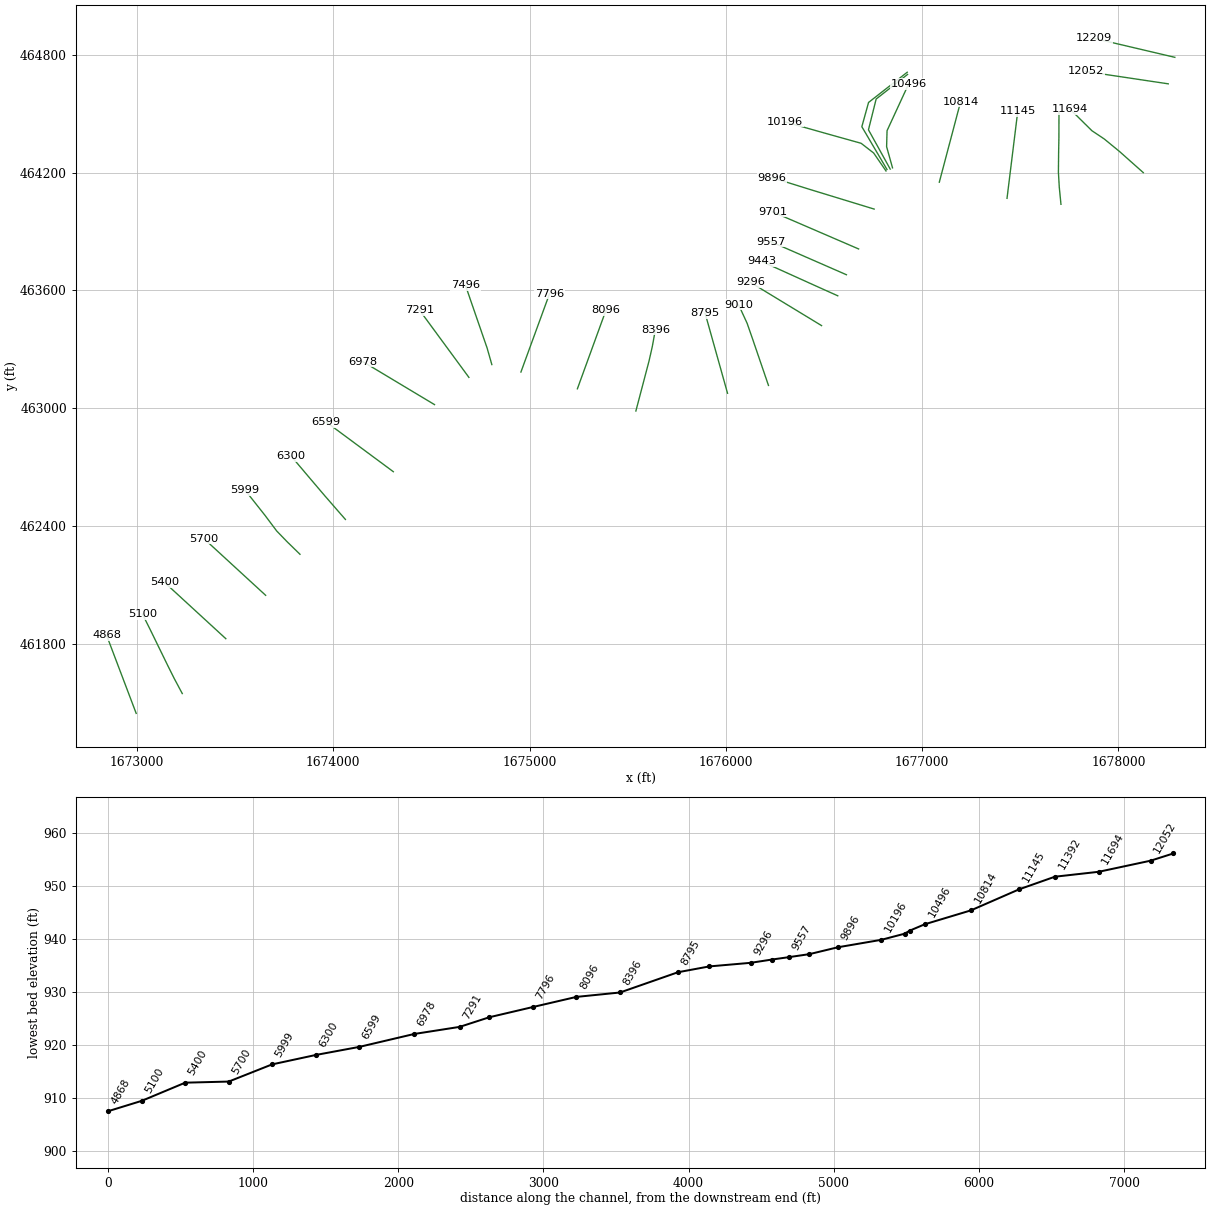
HEC-RAS study HrtRn.prj: HrtRn

--- HrtRn.g01 (geometry) --- (continued)

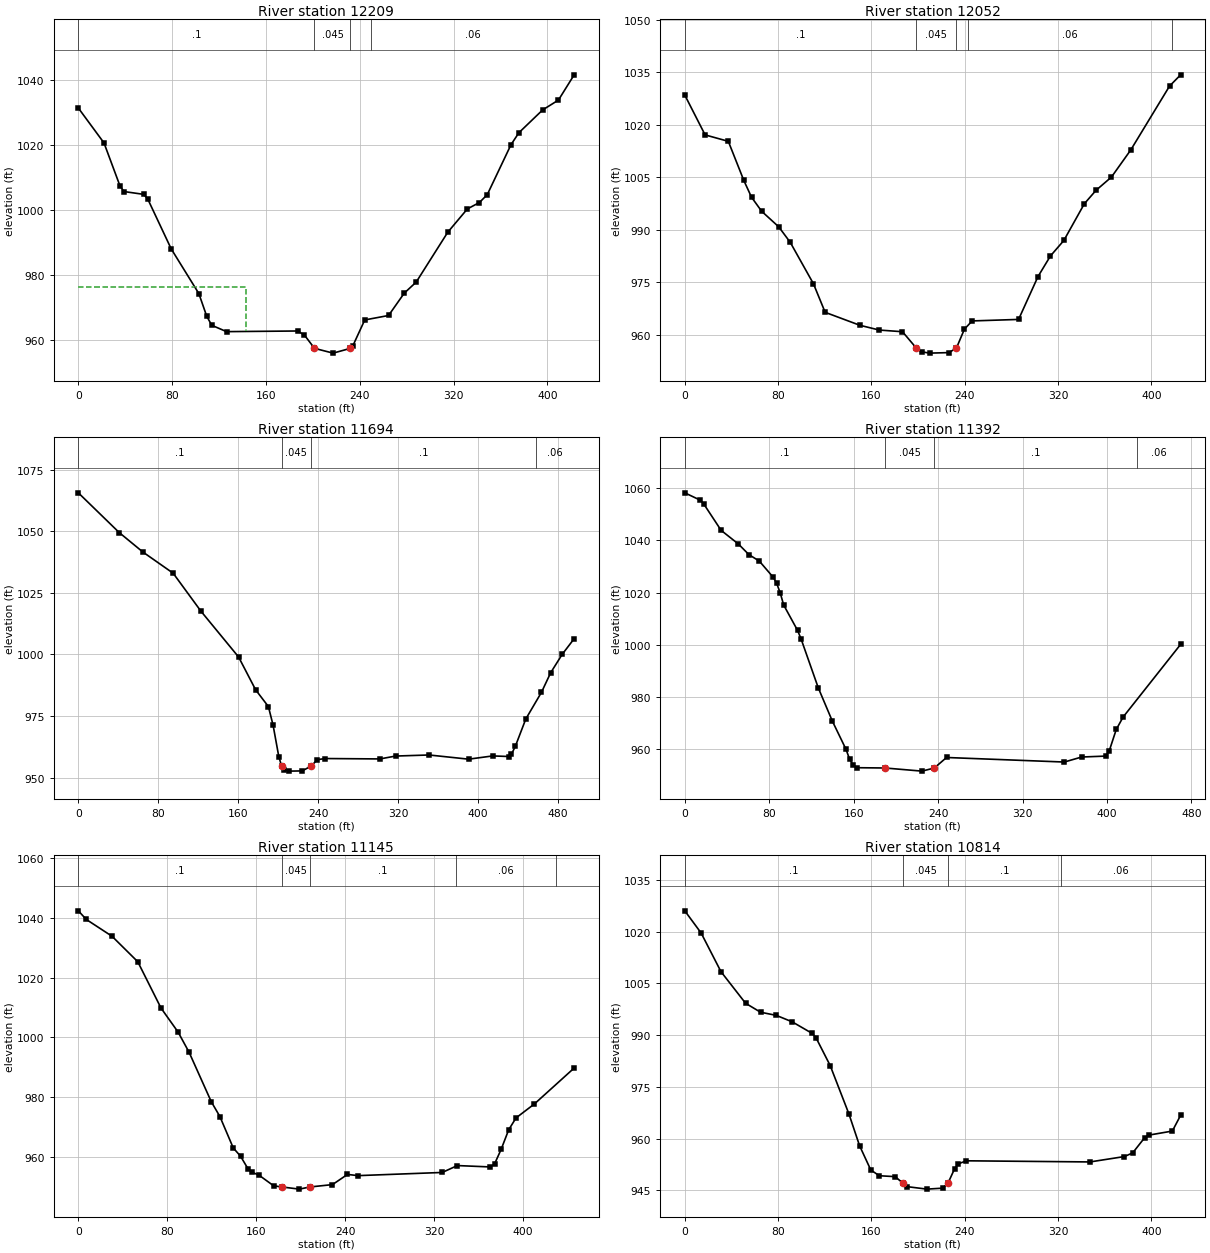
Type RM Length L Ch R = 1 ,12209   ,155.6,156.8,158.5
XS GIS Cut Line= 2
1678287.94322904464786.8976899931677876.26008585 464883.64816489
#Sta/Elev= 30
       0 1031.26    21.9 1020.55    35.4 1007.49    38.8 1005.65    55.6 1004.79
      59 1003.51    79.2  988.07   102.8  974.35   109.5  967.41   113.8  964.63
   126.4  962.68   187.1  962.88   192.9   961.6  201.43957.5539   217.3  956.09
  232.06957.5544   234.2  958.38   244.3  966.27   264.6  967.63     278  974.49
   288.2  977.89   315.1  993.17   331.8 1000.31   342.1 1002.28   348.8  1004.7
     369    1020   375.8  1023.7     396 1030.67   409.5  1033.7   422.9 1041.44
#Mann= 4 ,-1,0
       0      .1       0  201.43    .045       0  232.06      .1       0
     250     .06       0
#XS Ineff= 2 , 0
           142.6  976.37
Permanent Ineff=
       F       F
Bank Sta=201.43,232.06
XS Rating Curve= 0 ,0
Exp/Cntr(USF)=0,0
Exp/Cntr=0.3,0.1

Type RM Length L Ch R = 1 ,12052   ,362.9,358.2,346.3
XS GIS Cut Line= 6
1678254.32170119464651.8422223171678167.78348844464664.782485156
1678093.60843994464675.8743264811677994.70804719 464690.66301082
1677920.53267061 464701.754852161677833.99478594464714.695114984
#Sta/Elev= 30
       0 1028.53    17.4 1017.14    37.3  1015.3    50.6  1004.1    57.2  999.31
    65.9  995.29    80.5  990.85    90.4   986.4   110.3  974.54   120.3  966.39
   150.1  962.68   166.7  961.32   186.6  960.84  198.42956.1768   203.2  955.09
   209.8  954.72   226.4  954.87  232.84956.1759   239.7  961.59   246.3  963.93
   286.1  964.36   302.7  976.59   313.4  982.51   324.9  986.94   342.5  997.46
   352.5 1001.29   365.7 1005.08   382.3 1012.85   415.5  1031.1     425 1034.32
#Mann= 5 ,-1,0
       0      .1       0  198.42    .045       0  232.84      .1       0
   242.5     .06       0   417.5      .1       0
Bank Sta=198.42,232.84
XS Rating Curve= 0 ,0
Exp/Cntr(USF)=0,0
Exp/Cntr=0.3,0.1

Type RM Length L Ch R = 1 ,11694   ,314.9,302.1,282.7
XS GIS Cut Line= 6
1678127.29453184464199.3150094151678061.89636867464257.446782917
1678005.84037842464307.274111092  1677928.468814464370.750690177
 1677865.4669715 464412.861826421677753.15682053464523.836712145
#Sta/Elev= 30
       0 1065.55    40.9 1049.43    64.6 1041.53    94.9 1032.93   122.7 1017.52
   160.4  998.92   177.4  985.64   190.2  978.82   194.9  971.26   200.6  958.55
  203.41954.7014   205.8  953.08     211  952.62   224.1  952.71   233.1954.7053
   239.2  957.28   247.2  957.73   301.8  957.57   317.6  958.74     351  959.17
   390.6  957.47   414.7  958.79     431  958.55   433.3  959.37   437.3  962.66
   447.8  973.77   463.5  984.62   472.7  992.55   484.3 1000.05   496.2 1006.36
#Mann= 4 ,-1,0
       0      .1       0  203.41    .045       0   233.1      .1       0
  458.36     .06       0
Bank Sta=203.41,233.1
XS Rating Curve= 0 ,0
Exp/Cntr(USF)=0,0
Exp/Cntr=0.3,0.1

Type RM Length L Ch R = 1 ,11392   ,247.3,246.3,244.2
XS GIS Cut Line= 6
1677707.72184995464038.0887578041677699.09391445464126.164369053
 1677694.7284376464201.4158589751677695.78191319464301.414018563
1677697.22810453464376.4000890611677697.61996799464507.282053289
#Sta/Elev= 30
       0 1058.23    14.6 1055.43    17.9 1054.01    34.4 1043.87    50.8 1038.63
    60.7 1034.59    70.6  1032.1    83.8  1025.9    87.1 1023.52    90.4 1019.92
    93.7 1015.27   106.8  1005.6   110.1 1002.38   126.5  983.54   139.7  970.93
   152.8  959.99   156.1  956.31   159.4  954.14   162.7     953   189.7  952.89
   224.7  951.69   236.4952.8782     248  956.91   359.6  955.17     376  957.09
   398.9  957.45   402.2  959.49   408.8  967.63   415.3  972.39   469.8 1000.21
#Mann= 4 ,-1,0
       0      .1       0   189.7    .045       0   236.4      .1       0
  428.88     .06       0
Bank Sta=189.7,236.4
XS Rating Curve= 0 ,0
Exp/Cntr(USF)=0,0
Exp/Cntr=0.3,0.1

Type RM Length L Ch R = 1 ,11145   ,333.2,331.9,329.3
XS GIS Cut Line= 2
1677432.87723783464068.4407474761677487.52337586464511.259309524
#Sta/Elev= 30
       0 1042.28     7.2 1039.39    30.3 1033.79    53.5 1025.27    74.4  1009.8
    89.8 1001.76    99.7  995.01   119.6  978.54   127.4  973.55   139.4  963.08
     146   960.3   152.6  956.15   155.9  954.99   162.5     954   175.8  950.41
   183.3  950.03   198.9  949.31   208.2  950.02   228.7  950.82   242.2  954.22
   251.8  953.82   327.5  954.88   341.1  957.18   370.8  956.72   374.6  957.75
   380.5   962.6   387.3  969.15   393.9   973.1   410.5  977.79   446.2  989.76
#Mann= 5 ,-1,0
       0      .1       0   183.3    .045       0   208.2      .1       0
     340     .06       0     430      .1       0
Bank Sta=183.3,208.2
XS Rating Curve= 0 ,0
Exp/Cntr(USF)=0,0
Exp/Cntr=0.3,0.1

Type RM Length L Ch R = 1 ,10814   ,320.8,317.7,314.2
XS GIS Cut Line= 6
1677087.87501965464150.5911774021677110.26539482464235.177950484
1677129.45728556464307.6807582361677155.04647323464404.351168571
1677174.23836398464476.8543044011677196.62873914464561.441077498
#Sta/Elev= 30
       0    1026      14 1019.57      31 1008.37    52.1  999.21    64.9  996.62
    78.5  995.69    92.1  993.82   109.1  990.49   112.4  989.26   124.6  981.17
   140.7  967.11   149.8  957.93   159.4   950.9   166.7  949.22   180.3  948.96
  187.02 947.053   190.5  946.06   207.5  945.34     221  945.62  225.57947.0534
   231.2   951.2   234.6  952.69   241.4  953.55   347.3  953.22   376.8  954.78
   383.9  955.84   394.1  960.22   397.5  960.98   417.9  962.17     425  966.74
#Mann= 4 ,-1,0
       0      .1       0  187.02    .045       0  225.57      .1       0
   322.5     .06       0
Bank Sta=187.02,225.57
XS Rating Curve= 0 ,0
Exp/Cntr(USF)=0,0
Exp/Cntr=0.3,0.1

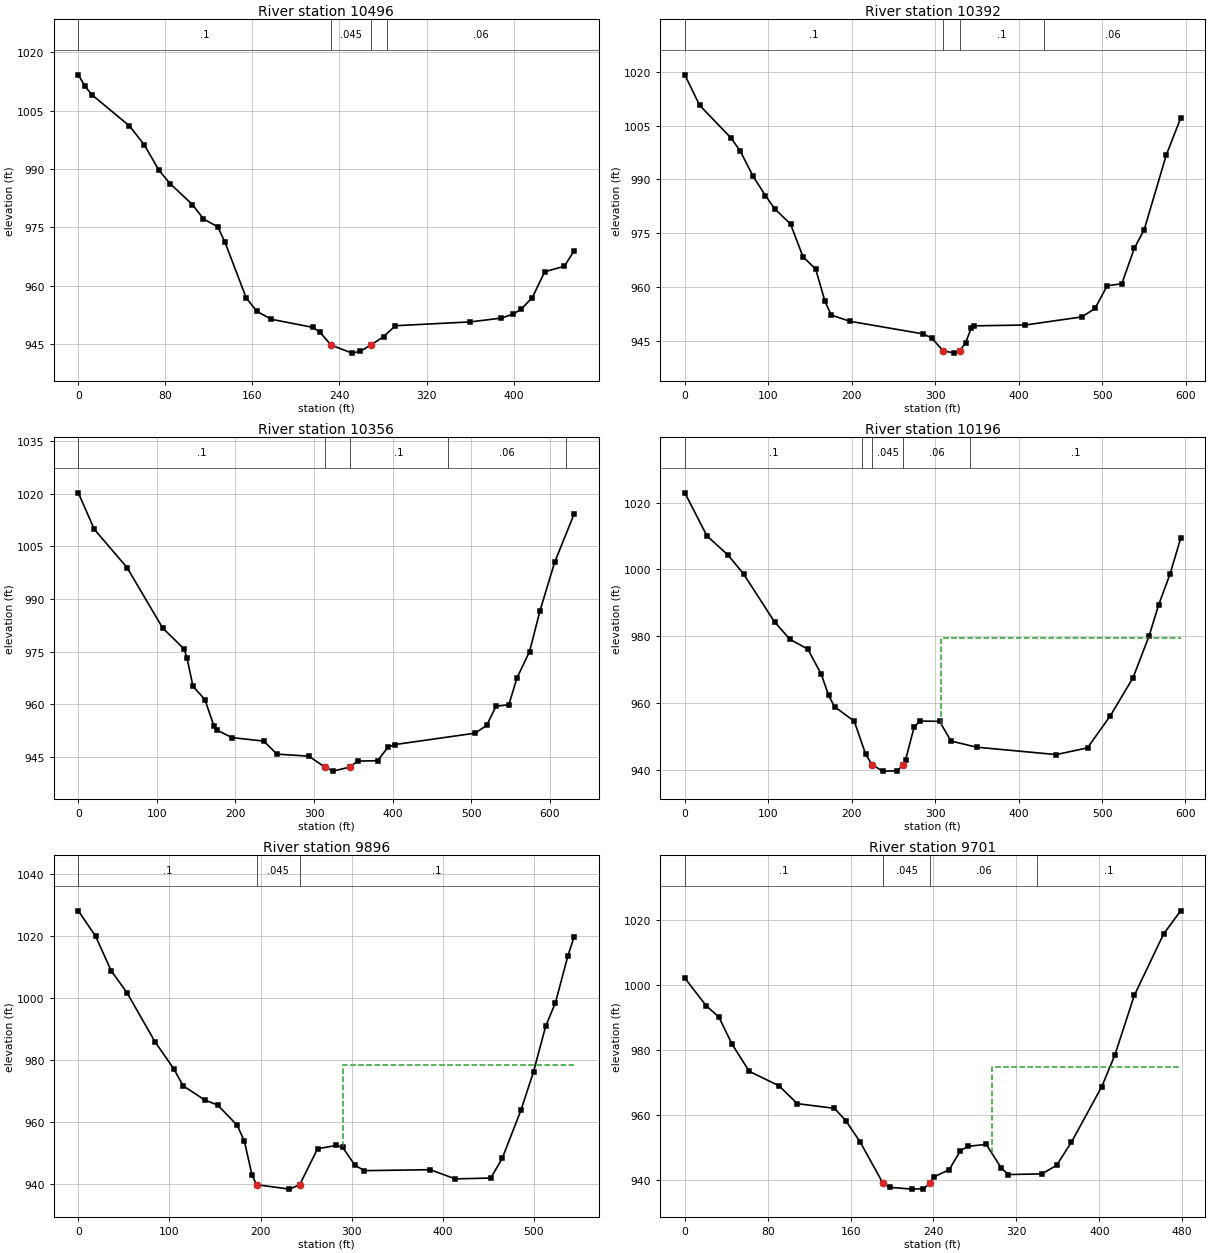
Type RM Length L Ch R = 1 ,10496   ,103.5,103.5,107.6
XS GIS Cut Line= 6
1676849.43488283464223.893372342  1676819.388355 464331.45614934
1676821.59701201464412.9874823391676863.50276808464503.783560589
1676894.93216717464571.8805372571676931.59974475464651.327228755
#Sta/Elev= 30
       0 1014.22     6.1 1011.27    12.9    1009      47 1001.08    60.6  996.25
    74.2  989.65    84.4  986.26   104.9  980.88     115  977.21   128.1  975.16
   134.7  971.27   154.4  956.84   164.2  953.45   177.3  951.42   215.5  949.34
   221.9  948.14   232.2944.7923   251.6  942.72     259  943.19  268.86 944.792
   280.5  946.95   291.4  949.76   360.4  950.75   388.9  951.72   399.8  952.77
     407  954.01   417.2  956.99   428.7  963.64   446.7  965.04   455.7  969.04
#Mann= 4 ,-1,0
       0      .1       0   232.2    .045       0  268.86      .1       0
  283.24     .06       0
Bank Sta=232.2,268.86
XS Rating Curve= 0 ,0
Exp/Cntr(USF)=0,0
Exp/Cntr=0.3,0.1

Type RM Length L Ch R = 1 ,10392   ,39.2,36.3,34.3
XS GIS Cut Line= 4
1676837.78530883464217.4406665171676726.91218489464417.671731379
1676766.12027732464574.4431660951676926.11551092464699.679843826
#Sta/Elev= 30
       0 1019.16    17.8 1010.65    55.3 1001.56    66.6  997.81    81.6  990.93
    96.6  985.44   107.8  981.74   126.6  977.54   141.6  968.35   156.6  965.02
   167.8  956.04   175.3  952.14   197.8   950.4   285.4  946.88   295.6  945.75
   309.1  942.22   322.6  941.52   329.4  942.22   336.2  944.43   342.9   948.4
   346.3  949.13   407.5  949.36   475.3  951.62   491.3  953.99   505.7  960.32
   523.2  960.86   538.4  970.84   550.1  975.97   576.5  996.76   593.7 1007.05
#Mann= 4 ,-1,0
       0      .1       0   309.1    .045       0   329.4      .1       0
  430.48     .06       0
Bank Sta=309.1,329.4
XS Rating Curve= 0 ,0
Exp/Cntr(USF)=0,0
Exp/Cntr=0.3,0.1

Type RM Length L Ch R = 1 ,10356   ,147,160.2,186.1
XS GIS Cut Line= 4
1676821.29254761 464215.566314631676693.19288314464433.420557476
1676727.35584307464556.9328218721676924.39829464464710.936110982
#Sta/Elev= 30
       0 1020.27    20.3 1009.87    62.1  998.93   107.3  981.74   134.5  975.77
   138.3  973.21   145.9  965.11   161.1  961.33   172.5  953.84   176.3  952.65
   195.4  950.49     236  949.49   252.7  945.78   293.3   945.2   313.7  942.09
     324  940.93  345.42942.0818   355.4  943.79   380.9   943.9   394.1  947.76
   402.4  948.49   504.9  951.75   519.8  953.98   531.5  959.44   547.9  959.84
   558.2  967.48   574.2  974.99   587.6  986.72   606.1 1000.41     631 1014.28
#Mann= 5 ,-1,0
       0      .1       0   313.7    .045       0  345.42      .1       0
  470.88     .06       0  620.88      .1       0
Bank Sta=313.7,345.42
XS Rating Curve= 0 ,0
Exp/Cntr(USF)=0,0
Exp/Cntr=0.3,0.1

Type RM Length L Ch R = 1 ,10196   ,300.4,300,299.8
XS GIS Cut Line= 6
1676816.39098567464207.8884830921676753.30023259464299.445714667
1676689.42142335464348.9669410881676593.10173409464375.847464755
1676520.86204918464396.0075294231676302.23741695464457.911765544
#Sta/Elev= 30
       0 1022.89    26.6 1010.01    51.9 1004.28    70.4  998.68   107.6  984.32
     126  979.15   147.4  976.21   163.5  968.74   172.4  962.37   179.5  959.01
   203.1  954.67   216.8  944.78  224.44941.6823   237.1  939.78   254.2  939.86
  261.95  941.68   264.5  943.09   274.7  952.81   281.5  954.74   305.3  954.64
     319  948.77   349.6  946.93   445.1  944.72   482.6  946.73   509.9  956.29
   537.1  967.64   556.3  980.07   567.8  989.38   581.5  998.63   594.2 1009.27
#Mann= 5 ,-1,0
       0      .1       0  212.02     .06       0  224.44    .045       0
  261.95     .06       0  342.02      .1       0
#XS Ineff= 2 , 0
                          307.63          979.54
Permanent Ineff=
       F       F
Bank Sta=224.44,261.95
XS Rating Curve= 0 ,0
Exp/Cntr(USF)=0,0
Exp/Cntr=0.3,0.1

Type RM Length L Ch R = 1 ,9896    ,197,195,191.8
XS GIS Cut Line= 6
1676755.88749775464013.7202362571676672.20656276464039.289082751
1676600.48032826464061.2057055831676504.84502085464090.427431926
1676433.11878633 464112.34372668 1676235.8843858464173.898154416
#Sta/Elev= 30
       0 1028.02      19 1019.81    36.1 1008.69    53.3 1001.68    84.1  985.85
   104.7  977.15     115  971.65     139  967.03   152.8  965.48   174.4  958.92
   182.3  953.73   190.5  943.01  195.53939.7997   231.7  938.37  242.93939.8005
   262.5  951.35   283.1  952.46     290  951.82   303.7  946.01     314  944.32
   386.1  944.63   413.6  941.67   452.6  941.94   465.2  948.29   485.8  963.88
   499.5  976.15   512.8   990.8   523.6  998.47   537.3 1013.61   544.1 1019.68
#Mann= 3 ,-1,0
       0      .1       0  195.53    .045       0  242.93      .1       0
#XS Ineff= 2 , 0
                          289.99          978.32
Permanent Ineff=
       F       F
Bank Sta=195.53,242.93
XS Rating Curve= 0 ,0
Exp/Cntr(USF)=0,0
Exp/Cntr=0.3,0.1

Type RM Length L Ch R = 1 ,9701    ,144.3,144.2,144.1
XS GIS Cut Line= 2
1676676.75164708463810.5076933281676237.42551107464000.059644147
#Sta/Elev= 30
       0 1002.11    20.5  993.63    32.9   990.1    45.4  981.83    62.2  973.37
    90.8  968.93   108.6  963.41   144.4  961.97   155.3  958.21   169.4  951.51
  191.27938.8741   197.7  937.64   219.4  937.08   230.2  937.19  236.63938.8715
   240.9  940.92   255.1  943.06   265.9  948.86     273  950.24   290.9  950.88
   305.5  943.53   312.3  941.58   344.5  941.76   358.8  944.41   373.1  951.53
   402.4  968.66   414.9  978.27   433.8  996.75     462 1015.63   478.5 1022.81
#Mann= 4 ,-1,0
       0      .1       0  191.27    .045       0  236.63     .06       0
     340      .1       0
#XS Ineff= 2 , 0
                           296.5          974.82
Permanent Ineff=
       F       F
Bank Sta=191.27,236.63
XS Rating Curve= 0 ,0
Exp/Cntr(USF)=0,0
Exp/Cntr=0.3,0.1

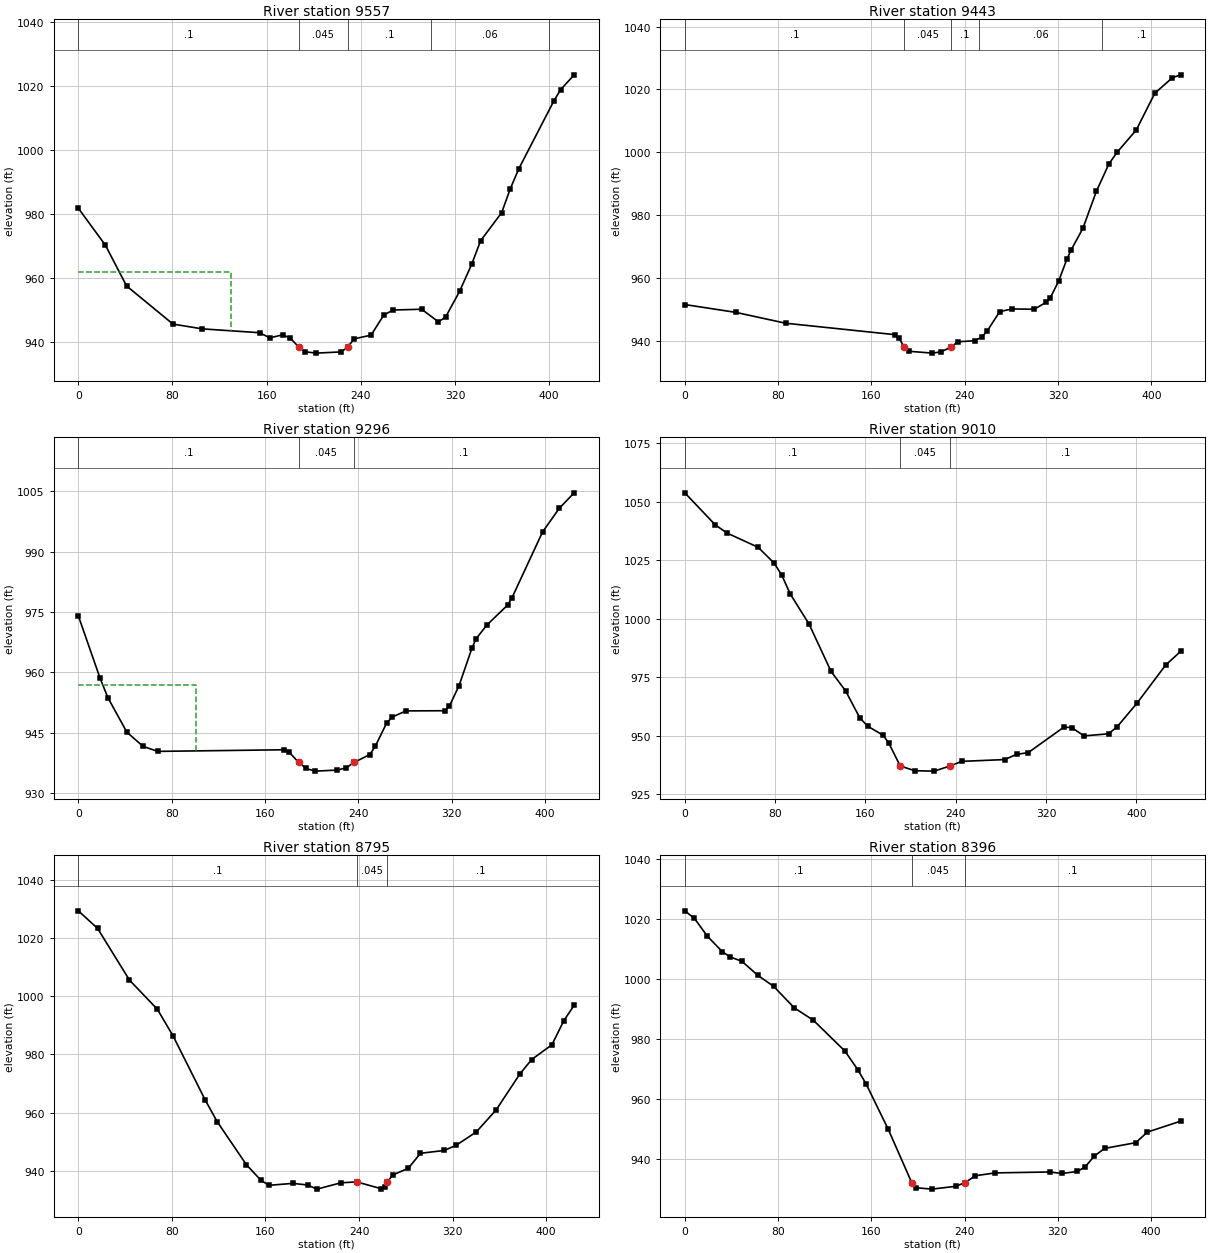
Type RM Length L Ch R = 1 ,9557    ,114,113.7,113.5
XS GIS Cut Line= 2
1676614.55491322463679.2034773961676228.54026337463848.023183594
#Sta/Elev= 30
       0  981.85      23  970.28      41  957.53    80.4  945.59   105.4  944.09
     154  942.89   162.6  941.28   173.5  942.21     180  941.24  187.22 938.426
   192.5  936.94   202.1   936.5   223.6  936.89  228.85938.4246   234.4  940.98
   248.7  942.12   259.4  948.33   267.2  949.99   291.7  950.24     306  946.29
   312.1  947.81   323.9  955.81   334.2  964.28   341.8  971.67   359.7  980.46
   366.9  987.84   374.3  994.24   404.2 1015.55   409.8 1018.97   421.3 1023.61
#Mann= 5 ,-1,0
       0      .1       0  187.22    .045       0  228.85      .1       0
     300     .06       0     400      .1       0
#XS Ineff= 2 , 0
          129.45  961.88
Permanent Ineff=
       F       F
Bank Sta=187.22,228.85
XS Rating Curve= 0 ,0
Exp/Cntr(USF)=0,0
Exp/Cntr=0.3,0.1

Type RM Length L Ch R = 1 ,9443    ,149.9,147.1,145
XS GIS Cut Line= 6
1676570.53053015  463571.85852271676490.69866881463607.680301459
1676422.34185015463638.5401478721676331.23113999463679.756928952
1676262.89794332463710.669596793 1676183.1759899463746.734485285
#Sta/Elev= 30
       0  951.52    43.6  949.04    86.4  945.58     180  941.94   183.6  940.81
  188.08938.0021   192.4  936.64   212.3  936.06   219.7  936.47  228.21 938.003
     234  939.66   248.4  940.01   254.4  941.12   259.2  943.11     270   949.3
   280.8  950.12   299.5  950.03   309.6  952.21   313.2  953.61   320.4  958.93
   327.6  966.07   331.2  968.93   341.2  975.77   352.8  987.58   363.6  996.33
   370.6 1000.01     387  1007.1   402.9  1018.8     418 1023.74     425 1024.64
#Mann= 5 ,-1,0
       0      .1       0  188.08    .045       0  228.21      .1       0
   252.5     .06       0   357.5      .1       0
Bank Sta=188.08,228.21
XS Rating Curve= 0 ,0
Exp/Cntr(USF)=0,0
Exp/Cntr=0.3,0.1

Type RM Length L Ch R = 1 ,9296    ,293.5,285.4,261.9
XS GIS Cut Line= 6
1676487.90509409 463420.061646671676413.13129351463465.505781502
1676349.03955817463504.457803339 1676263.5843485463556.393723086
1676199.49261317463595.3454168441676124.71881258463640.789551675
#Sta/Elev= 30
       0  974.06    18.6  958.57    25.4  953.67    41.6  945.13    55.6  941.57
    68.2  940.35   175.9  940.75   180.6  940.21  188.83937.6053   195.2   936.1
   202.9  935.44   222.1   935.7   229.8  936.29  236.25937.6046   249.9  939.56
   254.7  941.72   264.2  947.36     269  948.88   280.9  950.42   314.2  950.46
   318.1  951.65   326.3  956.67   337.5  966.12   341.1  968.42   350.2  971.78
     368  976.75   371.7  978.55   397.9  994.91   412.3 1000.82     425 1004.65
#Mann= 3 ,-1,0
       0      .1       0  188.83    .045       0  236.25      .1       0
#XS Ineff= 2 , 0
          100.62   956.8
Permanent Ineff=
       F       F
Bank Sta=188.83,236.25
XS Rating Curve= 0 ,0
Exp/Cntr(USF)=0,0
Exp/Cntr=0.3,0.1

Type RM Length L Ch R = 1 ,9010    ,214.5,215.7,206
XS GIS Cut Line= 4
1676217.48834837463115.1420436231676134.91030513463356.563324975
1676108.55340246463432.0470978931676064.91011705463526.673549058
#Sta/Elev= 30
       0 1053.82    26.8 1040.21    37.2 1036.66      65 1030.51    78.9 1023.87
    85.7 1018.83    93.4 1010.57   110.1  997.67   129.6  977.41   142.5  969.07
   155.1   957.5   162.1  953.99   175.9  950.04   180.9  946.59  190.85936.9717
   203.7  934.93     221  934.76  234.97936.9698   245.3  938.93   283.5  939.71
   293.9  941.92   304.3  942.68     336  953.63   342.9  953.36   353.7  949.82
   375.4  950.73     383  953.69   400.7  963.86     426  980.12   439.3  985.98
#Mann= 3 ,-1,0
       0      .1       0  190.85    .045       0  234.97      .1       0
Bank Sta=190.85,234.97
XS Rating Curve= 0 ,0
Exp/Cntr(USF)=0,0
Exp/Cntr=0.3,0.1

Type RM Length L Ch R = 1 ,8795    ,406.5,398.9,380.7
XS GIS Cut Line= 2
1676008.81577384463075.4593728431675894.45620894463483.626555217
#Sta/Elev= 30
       0 1029.42    16.5 1023.35    43.7  1005.6    67.6  995.53    81.2  986.22
   108.5   964.3   118.7  956.88   143.7  942.05   156.1  936.71     163  934.97
   183.4  935.64     196  935.08     204  933.66   224.3  935.82   237.9  936.16
   258.4  933.86   261.8  934.53  264.18936.0677   268.6  938.47   282.2  940.87
   292.5  945.99   312.9  946.97   323.1  948.77   340.2  953.32   357.2  960.92
   377.6  973.35   387.6  978.26   404.9  983.34   415.1  991.64   423.9  996.93
#Mann= 3 ,-1,0
       0      .1       0   237.9    .045       0  264.18      .1       0
Bank Sta=237.9,264.18
XS Rating Curve= 0 ,0
Exp/Cntr(USF)=0,0
Exp/Cntr=0.3,0.1

Type RM Length L Ch R = 1 ,8396    ,301.4,300,297.2
XS GIS Cut Line= 6
1675541.87647434462984.8400761781675564.14447442463069.459001422
1675583.23137851463141.9896962491675608.68080267463238.697180003
1675625.31265917463311.8738709241675641.11872992463398.193252087
#Sta/Elev= 30
       0 1022.64     8.3 1020.09    19.4 1014.17    32.1 1009.03    38.9 1007.27
      49 1005.81    62.6 1001.14    76.2  997.46    93.9  990.29   110.3  986.14
   137.3   975.9   148.4  969.67   155.7  964.79   174.5  949.79   194.7931.9637
   198.3  930.31   211.9  929.84   232.2  930.77  240.25931.9662   249.2   934.3
   266.1  935.25   313.2  935.56   323.4  935.06   336.8  935.73   343.5   937.3
   351.2  940.83   360.1  943.42   386.8  945.33   396.8  948.86   425.3   952.5
#Mann= 3 ,-1,0
       0      .1       0   194.7    .045       0  240.25      .1       0
Bank Sta=194.7,240.25
XS Rating Curve= 0 ,0
Exp/Cntr(USF)=0,0
Exp/Cntr=0.3,0.1

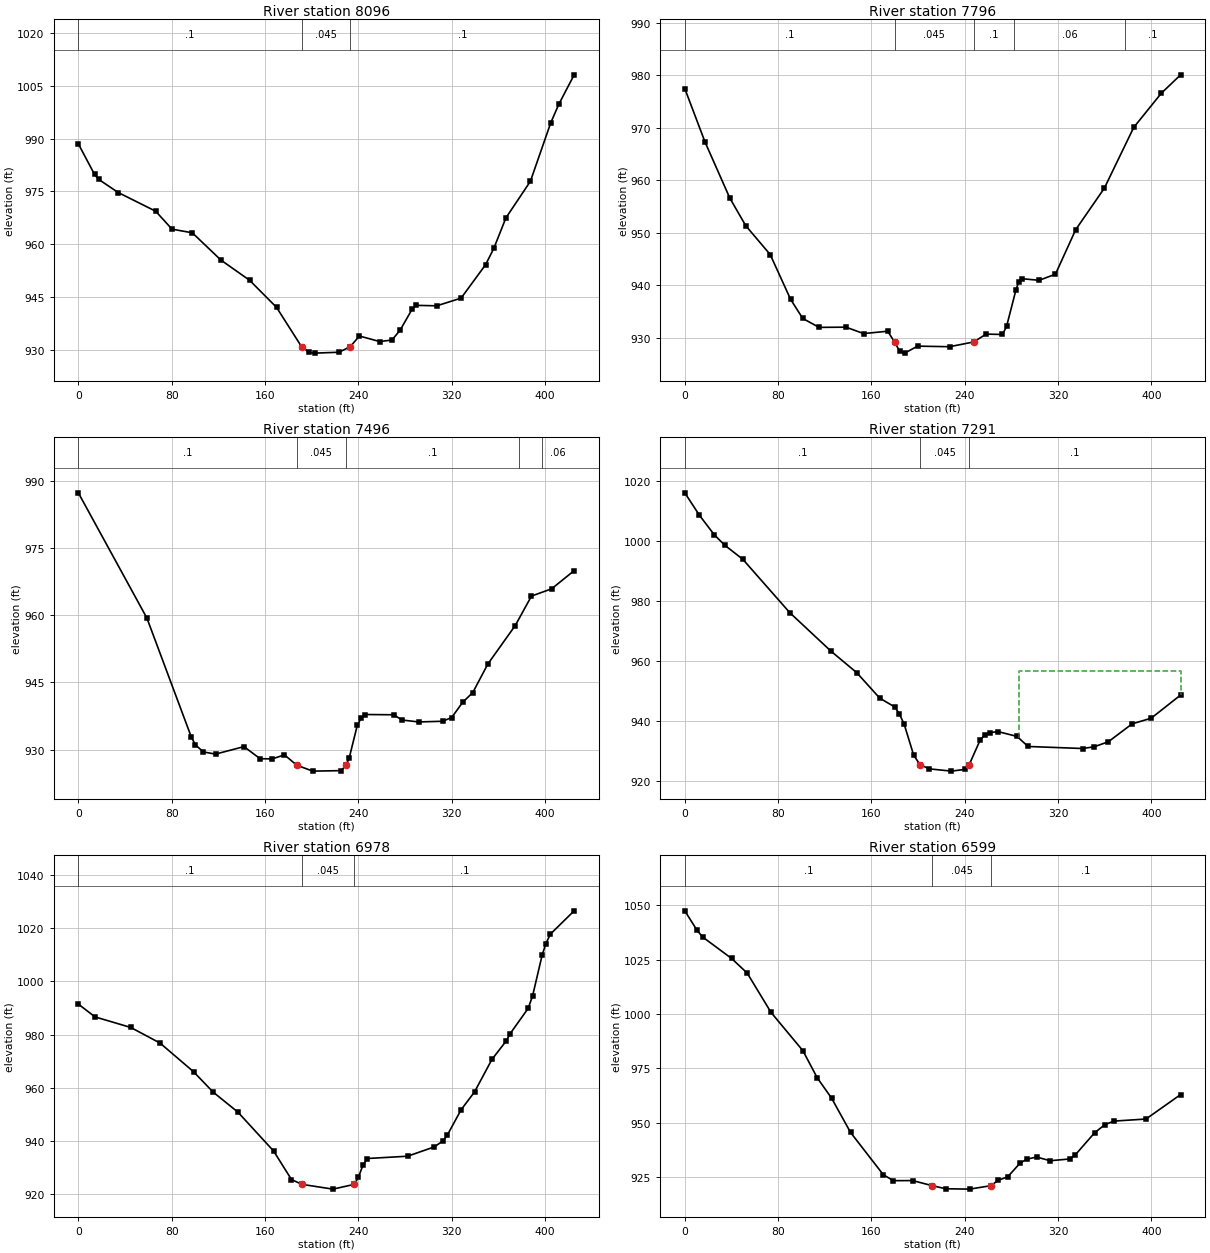
Type RM Length L Ch R = 1 ,8096    ,301,300,299.3
XS GIS Cut Line= 6
1675243.83901267463097.9057949191675273.74118385463180.137913927
   1675299.37171463250.6223530021675333.54585426463344.601823837
1675359.17638043463415.0865910051675389.07855159 463497.31838192
#Sta/Elev= 30
       0  988.51    13.9   979.8    17.4  978.41    34.2  974.67    66.3  969.35
    80.3  964.25    97.7  963.22   122.2  955.47   146.8  949.72   169.9  942.02
   191.3930.8611     198  929.21   202.5  929.01   223.4  929.26  233.16930.8621
   240.9  933.88   258.3   932.3   268.8  932.73   275.8  935.52   286.2  941.55
   289.7  942.59   307.2  942.46   328.1  944.65   349.1  954.16   356.1  958.77
   366.5  967.45   387.5  977.87   404.9  994.46   411.9   999.8     425 1008.13
#Mann= 3 ,-1,0
       0      .1       0   191.3    .045       0  233.16      .1       0
Bank Sta=191.3,233.16
XS Rating Curve= 0 ,0
Exp/Cntr(USF)=0,0
Exp/Cntr=0.3,0.1

Type RM Length L Ch R = 1 ,7796    ,280,300,314.5
XS GIS Cut Line= 6
1674956.17029667463183.3436161731674986.19976418463265.529147342
1675011.93921401463335.9742164161675046.25837108463429.900537759
1675071.99782093463500.345278755 1675102.0276165463582.531138003
#Sta/Elev= 30
       0  977.44    17.3  967.29    38.6   956.6    52.2  951.36    73.2  945.86
    90.7  937.33   101.1   933.7   115.1     932   138.1  932.04   153.3  930.82
   173.9  931.27  179.78929.2233   184.2  927.46   188.5   927.1   199.5  928.43
   226.9  928.32  247.61929.2258   258.3  930.72   272.3  930.65   275.8  932.18
   283.9  939.18   286.3  940.69     289  941.26   303.7  940.96   317.7  942.12
   335.1  950.61   359.6  958.48   384.8  970.05   408.5  976.57     425  980.06
#Mann= 5 ,-1,0
       0      .1       0  179.78    .045       0  247.61      .1       0
   282.5     .06       0   377.5      .1       0
Bank Sta=179.78,247.61
XS Rating Curve= 0 ,0
Exp/Cntr(USF)=0,0
Exp/Cntr=0.3,0.1

Type RM Length L Ch R = 1 ,7496    ,198.1,205,210.8
XS GIS Cut Line= 6
1674807.93896584463221.3904560951674783.89669108463305.658660263
1674759.40789492463376.5482822511674726.75572926463471.067450166
1674702.26693308 463541.956744091674673.69645217463624.660975009
#Sta/Elev= 30
       0   987.4    58.8  959.39    96.9  932.77   100.4  931.03   107.3  929.45
   117.7  928.98     142  930.65   155.9  927.94   166.3  927.91   176.7  928.81
  187.25 926.499     201  925.17   225.3  925.28   229.6926.5009   232.3  928.18
   239.2  935.45   242.7  937.12   246.2  937.83   270.5  937.77   277.4   936.6
   291.8  936.17   312.4  936.32   320.1  937.16   329.5  940.55   338.2  942.75
   351.1  949.12   374.6  957.73   388.5  964.31   405.8  965.94   425.1     970
#Mann= 5 ,-1,0
       0      .1       0  187.25    .045       0   229.6      .1       0
  377.63     .05       0  397.63     .06       0
Bank Sta=187.25,229.6
XS Rating Curve= 0 ,0
Exp/Cntr(USF)=0,0
Exp/Cntr=0.3,0.1

Type RM Length L Ch R = 1 ,7291    ,301.5,313.1,319.2
XS GIS Cut Line= 6
1674691.03443882463156.2807967271674639.24254765463226.806246227
1674594.84959182463287.2565846351674535.65843724463367.856817147
1674491.26515332463428.3071555551674439.47326215463498.832605055
#Sta/Elev= 30
       0 1016.14    12.6 1008.63    25.2 1002.19    34.1  998.72    49.7  993.99
      90  976.18   125.2  963.38   147.4  956.17   167.1  947.68   179.9  944.75
   183.8  942.52   188.1  938.92   196.2  928.65  201.66 925.479   209.7   924.1
   228.5  923.35   240.2  923.93  243.76925.4812   253.2  933.74   257.3  935.46
   261.3  936.16   268.4  936.54   284.8  934.92   294.2  931.57   341.1  930.89
   350.9  931.47   363.1  933.15   383.4  939.11   399.7  940.98     425  948.72
#Mann= 3 ,-1,0
       0      .1       0  201.66    .045       0  243.76      .1       0
#XS Ineff= 2 , 0
                           286.6           956.8
Permanent Ineff=
       F       F
Bank Sta=201.66,243.76
XS Rating Curve= 0 ,0
Exp/Cntr(USF)=0,0
Exp/Cntr=0.3,0.1

Type RM Length L Ch R = 1 ,6978    ,381.4,378.7,377
XS GIS Cut Line= 6
 1674515.8357134463017.4556545741674440.80502357463062.474265319
1674376.49314432463101.0614584961674290.74397199463152.510830653
1674226.43176466463191.0980238291674151.40140291463236.116306496
#Sta/Elev= 30
       0  991.51    14.3   986.7      45  982.72      70  976.88    98.9  966.05
   115.4  958.51   136.8  950.92   167.4  936.31   182.7  925.61  191.65923.8054
   218.2  922.01  236.64923.8071   240.1  926.52   243.9  930.91   247.7  933.51
   282.2  934.37   305.1  937.87   312.8   940.2   316.3  942.32   328.2   951.9
   339.6  958.51   354.5  970.72   366.5  977.52   370.2  980.44   385.5  989.86
   389.3  994.46   397.6 1009.98   400.8 1014.25   404.6 1017.78     425 1026.54
#Mann= 3 ,-1,0
       0      .1       0  191.65    .045       0  236.64      .1       0
Bank Sta=191.65,236.64
XS Rating Curve= 0 ,0
Exp/Cntr(USF)=0,0
Exp/Cntr=0.3,0.1

Type RM Length L Ch R = 1 ,6599    ,304.7,298.9,294.5
XS GIS Cut Line= 6
1674306.08793542462675.6609045121674235.75146192462727.709684923
1674175.46352476462772.3227846771674095.07917109462831.807245761
1674034.79123393  462876.42034551673964.45476042462928.469125926
#Sta/Elev= 30
       0 1047.41    10.6 1038.38    15.3 1035.38    40.1 1025.53    53.5  1018.8
    73.9 1000.76   101.3   983.1   113.5  970.72   125.8  961.37   142.1  945.59
   170.1  926.22   178.8  923.45   195.2   923.5  212.05921.1635   223.7  919.74
   244.1  919.57  262.46921.1641   268.6  923.63   276.8  925.23   287.4  931.53
   293.1  933.32   301.5  934.31   313.2  932.62   329.9  933.42   334.8  935.36
   351.3  945.47   360.1   949.2   367.9  950.82   395.3  951.77     425  963.01
#Mann= 3 ,-1,0
       0      .1       0  212.05    .045       0  262.46      .1       0
Bank Sta=212.05,262.46
XS Rating Curve= 0 ,0
Exp/Cntr(USF)=0,0
Exp/Cntr=0.3,0.1

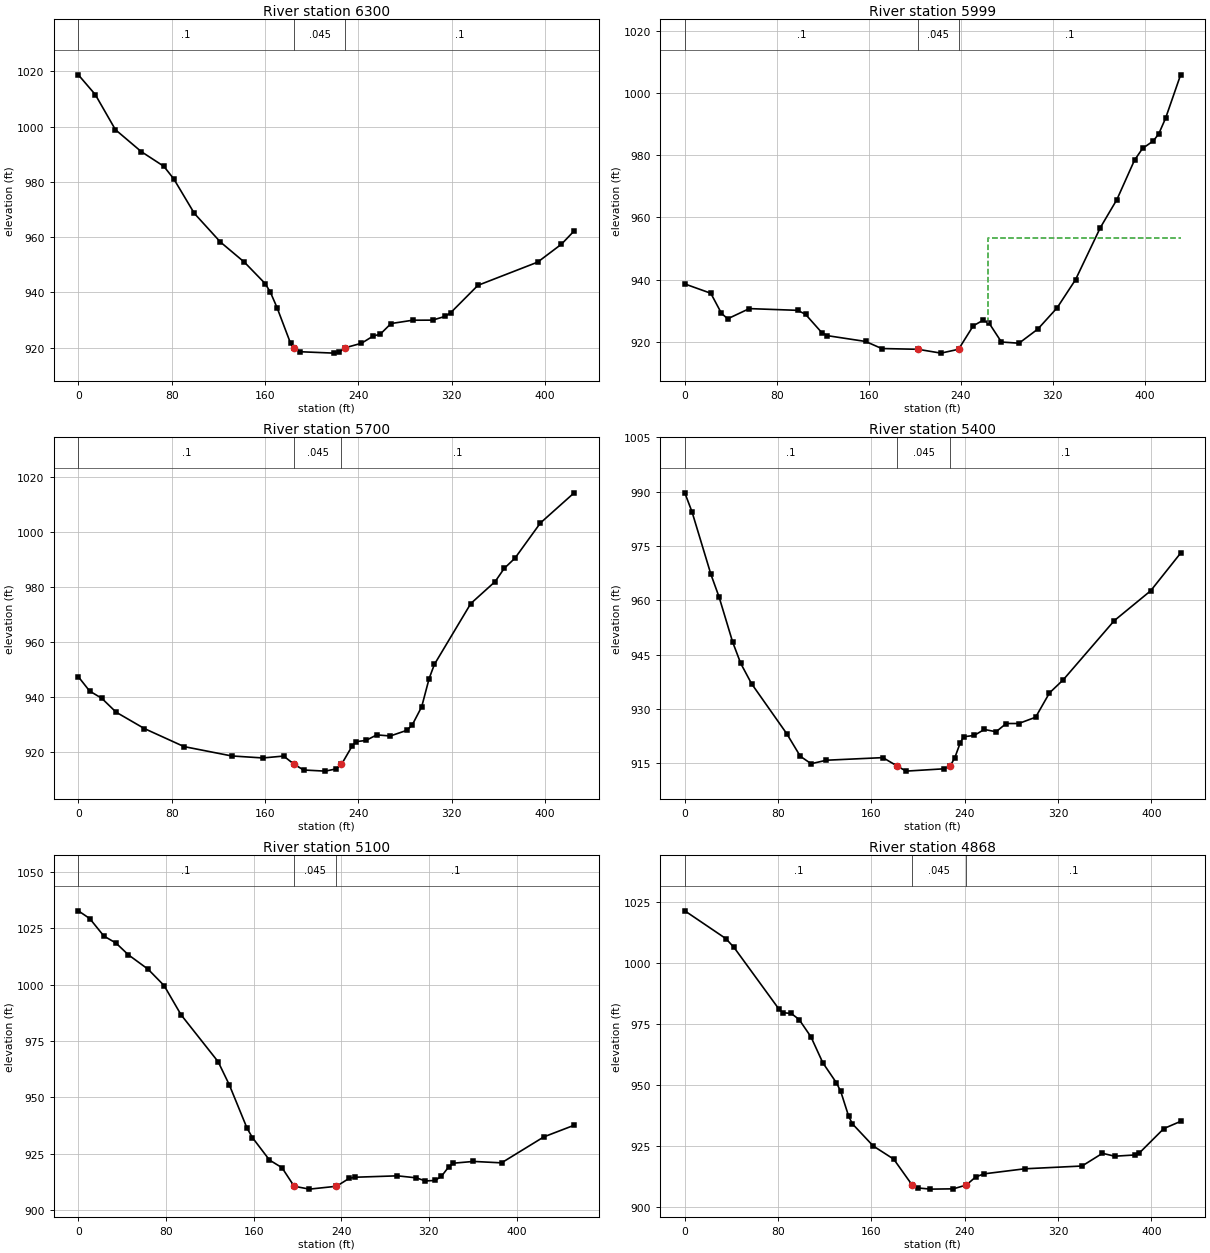
Type RM Length L Ch R = 1 ,6300    ,303.5,301.5,300.4
XS GIS Cut Line= 6
1674061.87516926462432.425170511 1674004.3451006462498.366639674
1673955.15195751 462554.988573671673890.31842576462631.124576256
1673841.87265651462688.3783987611673785.35275643462755.174853086
#Sta/Elev= 30
       0 1018.77    14.5 1011.64    31.8  998.91      54  990.96    73.3  985.66
    81.8  981.11    99.4  968.64   121.8  958.25   142.4  950.94   160.2  943.19
   164.6  940.11   170.3  934.55   181.9  921.62  184.65920.0068   190.4  918.55
   219.1  918.05   223.8  918.48  228.82 920.006   242.7  921.62   252.9  924.28
   258.7  924.86     268  928.75   286.6  929.96   303.6  929.99   314.6  931.38
   319.2  932.69   342.5  942.58   393.7  950.98   414.1  957.47     425  962.28
#Mann= 3 ,-1,0
       0      .1       0  184.65    .045       0  228.82      .1       0
Bank Sta=184.65,228.82
XS Rating Curve= 0 ,0
Exp/Cntr(USF)=0,0
Exp/Cntr=0.3,0.1

Type RM Length L Ch R = 1 ,5999    ,293.2,298.6,300.2
XS GIS Cut Line= 6
 1673830.3926926462254.9455385951673765.10640584462318.559912667
1673711.28236651462374.2287645941673651.37205325462454.343105674
1673604.81965293462513.1464657491673550.50808176462581.750659257
#Sta/Elev= 30
       0  938.57    22.6  935.57    31.9  929.08    37.3  927.34    56.1  930.62
    98.2  930.06     105  928.77   119.1  922.88   123.8  921.91   157.2  920.03
   171.2  917.75   202.7917.5079   222.7  916.27  238.01917.5065   250.8  925.08
   259.1  926.82   264.6  925.92   275.3  919.85   290.6  919.47     307  924.04
   323.7  930.87   339.7  939.93   361.3  956.73   375.7  965.78     391  978.47
     398  982.25   407.4  984.68   412.1  986.97     418  991.97   431.1 1005.98
#Mann= 3 ,-1,0
       0      .1       0   202.7    .045       0  238.01      .1       0
#XS Ineff= 2 , 0
                          263.43          953.45
Permanent Ineff=
       F       F
Bank Sta=202.7,238.01
XS Rating Curve= 0 ,0
Exp/Cntr(USF)=0,0
Exp/Cntr=0.3,0.1

Type RM Length L Ch R = 1 ,5700    ,300,300,300
XS GIS Cut Line= 6
1673655.44717634462045.8065211771673591.01423433462105.006205916
1673535.78567025462155.7488865851673462.14802226462223.406231582
1673406.87451075462274.1640040871673342.45731676462333.349253178
#Sta/Elev= 30
       0  947.36     9.7  942.14    20.1  939.51    32.4  934.46    56.6  928.51
    90.6  921.95   131.4  918.55   158.2  917.82     176  918.51  185.11915.4695
   193.1  913.44   211.6  913.03     221  913.84  225.55915.4717   234.9  922.31
   238.4  923.77   246.5  924.18   255.8  926.21   267.4  925.81   281.4  927.84
     286  929.65   294.3  936.42   300.7  946.71   305.2  951.84   336.4  973.97
   357.3  981.97     365  986.72   374.3  990.49   396.1 1003.28     425 1014.23
#Mann= 3 ,-1,0
       0      .1       0  185.11    .045       0  225.55      .1       0
Bank Sta=185.11,225.55
XS Rating Curve= 0 ,0
Exp/Cntr(USF)=0,0
Exp/Cntr=0.3,0.1

Type RM Length L Ch R = 1 ,5400    ,299.1,299.5,286.6
XS GIS Cut Line= 6
1673452.47612558461824.892921001 1673388.0428555461884.092605755
1673332.81461951461934.8356145021673259.17664342 462002.49263142
1673203.93200326462053.2241572591673139.50037359462112.422529668
#Sta/Elev= 30
       0  989.68     6.2  984.41    22.4  967.15    29.4  960.89      41  948.49
    47.9   942.6    57.2  936.98    87.4  923.15      99  916.93   108.3  914.86
   121.3  915.83   169.8  916.55  181.47914.3394   189.6  912.82   222.1  913.46
  227.64914.3409   231.4  916.49     236  920.55     239  922.32   247.9  922.66
   256.8  924.33   266.8  923.69   275.5  925.97   286.2  925.97   300.7   927.7
   312.6  934.43   324.3  938.01   368.1  954.37   399.3  962.62     425  973.03
#Mann= 3 ,-1,0
       0      .1       0  181.47    .045       0  227.64      .1       0
Bank Sta=181.47,227.64
XS Rating Curve= 0 ,0
Exp/Cntr(USF)=0,0
Exp/Cntr=0.3,0.1

Type RM Length L Ch R = 1 ,5100    ,233.8,232.3,230
XS GIS Cut Line= 5
1673230.69966626461545.2474829261673189.46123168461622.398247257
1673155.97967134461689.4804621791673069.73594698461866.124422333
1673027.94853804461949.856324879
#Sta/Elev= 30
       0 1032.67    10.4 1029.25    23.3  1021.5    34.4 1018.38    45.6 1013.22
    63.7 1006.79    78.3  999.55    93.8  986.59   127.6  965.84   137.8   955.6
     154  936.39   158.9  932.22   174.5  922.27   185.9  918.89  197.01910.6558
     211  909.39  235.65910.6553   247.2  914.15   252.1  914.65   291.3  915.28
   308.5  914.39   316.8  913.01   325.7  913.23   331.5   915.1     338  919.19
   342.4  920.88   360.7  921.66   386.3  921.03     425  932.55   452.6  937.69
#Mann= 3 ,-1,0
       0      .1       0  197.01    .045       0  235.65      .1       0
Bank Sta=197.01,235.65
XS Rating Curve= 0 ,0
Exp/Cntr(USF)=0,0
Exp/Cntr=0.3,0.1

Type RM Length L Ch R = 1 ,4868    ,380.2,368.2,344.2
XS GIS Cut Line= 6
1672995.89017947461444.253471814 1672964.8738373 461526.07187774
1672938.28858864461596.2016587331672902.84148106461689.708361484
 1672876.2559043461759.8384705711672845.23989021461841.656876482
#Sta/Elev= 30
       0 1021.32    35.2 1009.95    42.2 1006.33    80.8  981.04    84.3  979.63
    91.3  979.31      98  976.83   108.1  969.78   118.3  959.14   129.9  950.98
   133.6  947.51   140.5  937.18   143.7  934.13   161.5  925.09   179.1  919.69
  194.85909.1172   200.1   907.9   210.6  907.43   230.2  907.55  241.36 909.118
   249.2  912.37   256.3  913.67   291.3  915.75   340.5  916.89     358  922.09
   368.5   920.9   386.1  921.42   389.6  922.21   410.6  932.21     425  935.16
#Mann= 3 ,-1,0
       0      .1       0  194.85    .045       0  241.36      .1       0
Bank Sta=194.85,241.36
XS Rating Curve= 0 ,0
Exp/Cntr(USF)=0,0
Exp/Cntr=0.3,0.1