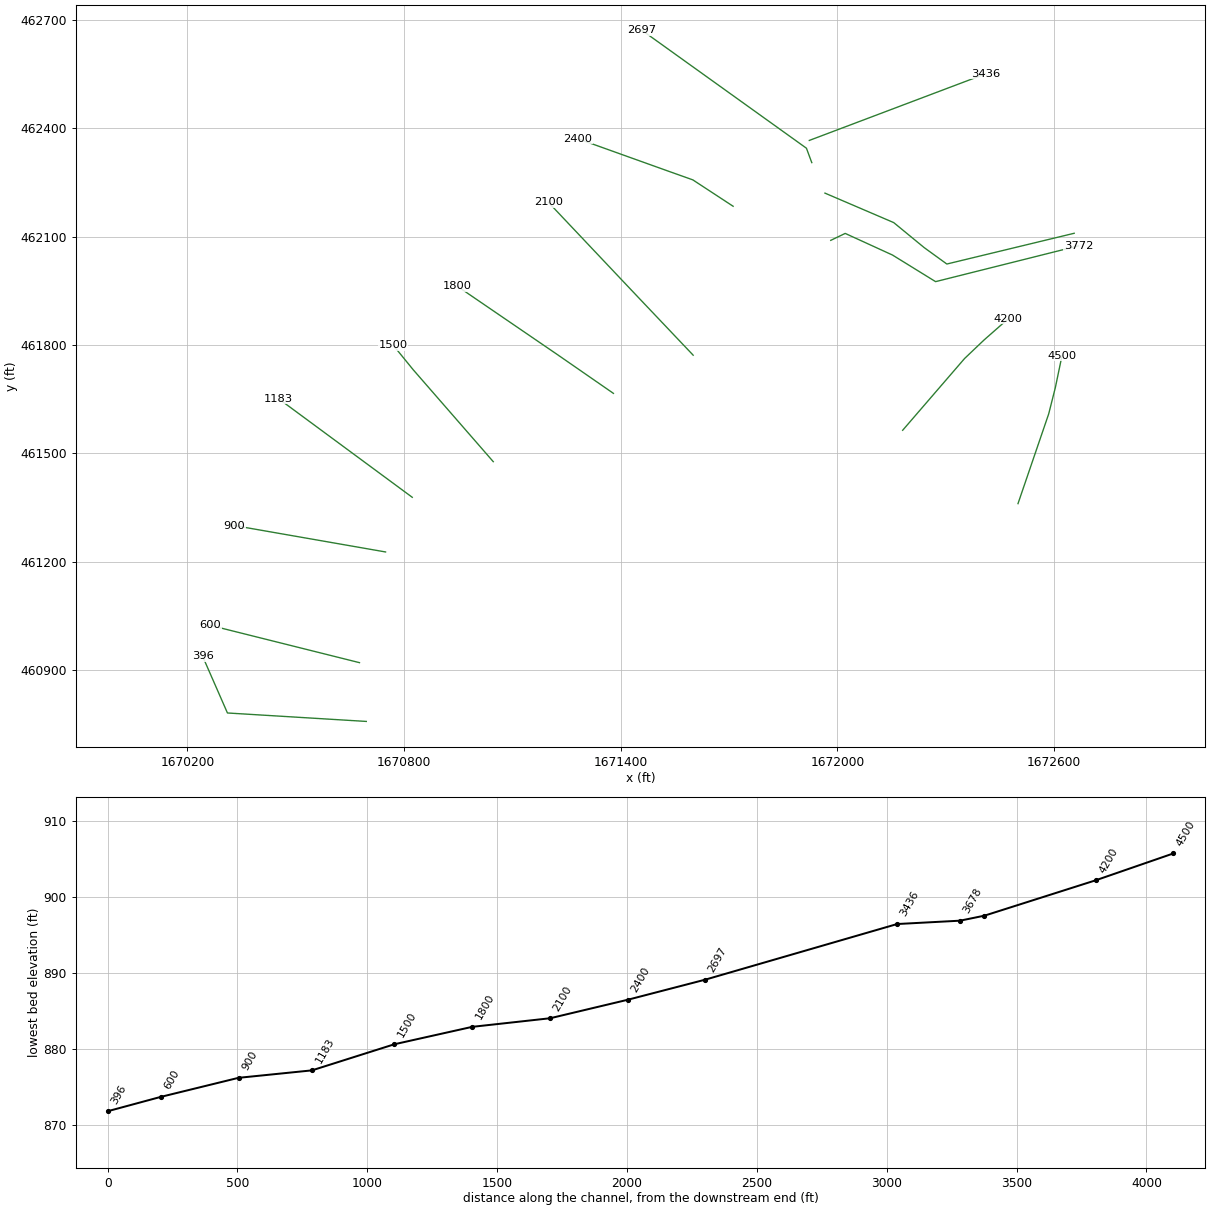
HEC-RAS study HrtRn.prj: HrtRn

--- HrtRn.g01 (geometry) --- (continued)

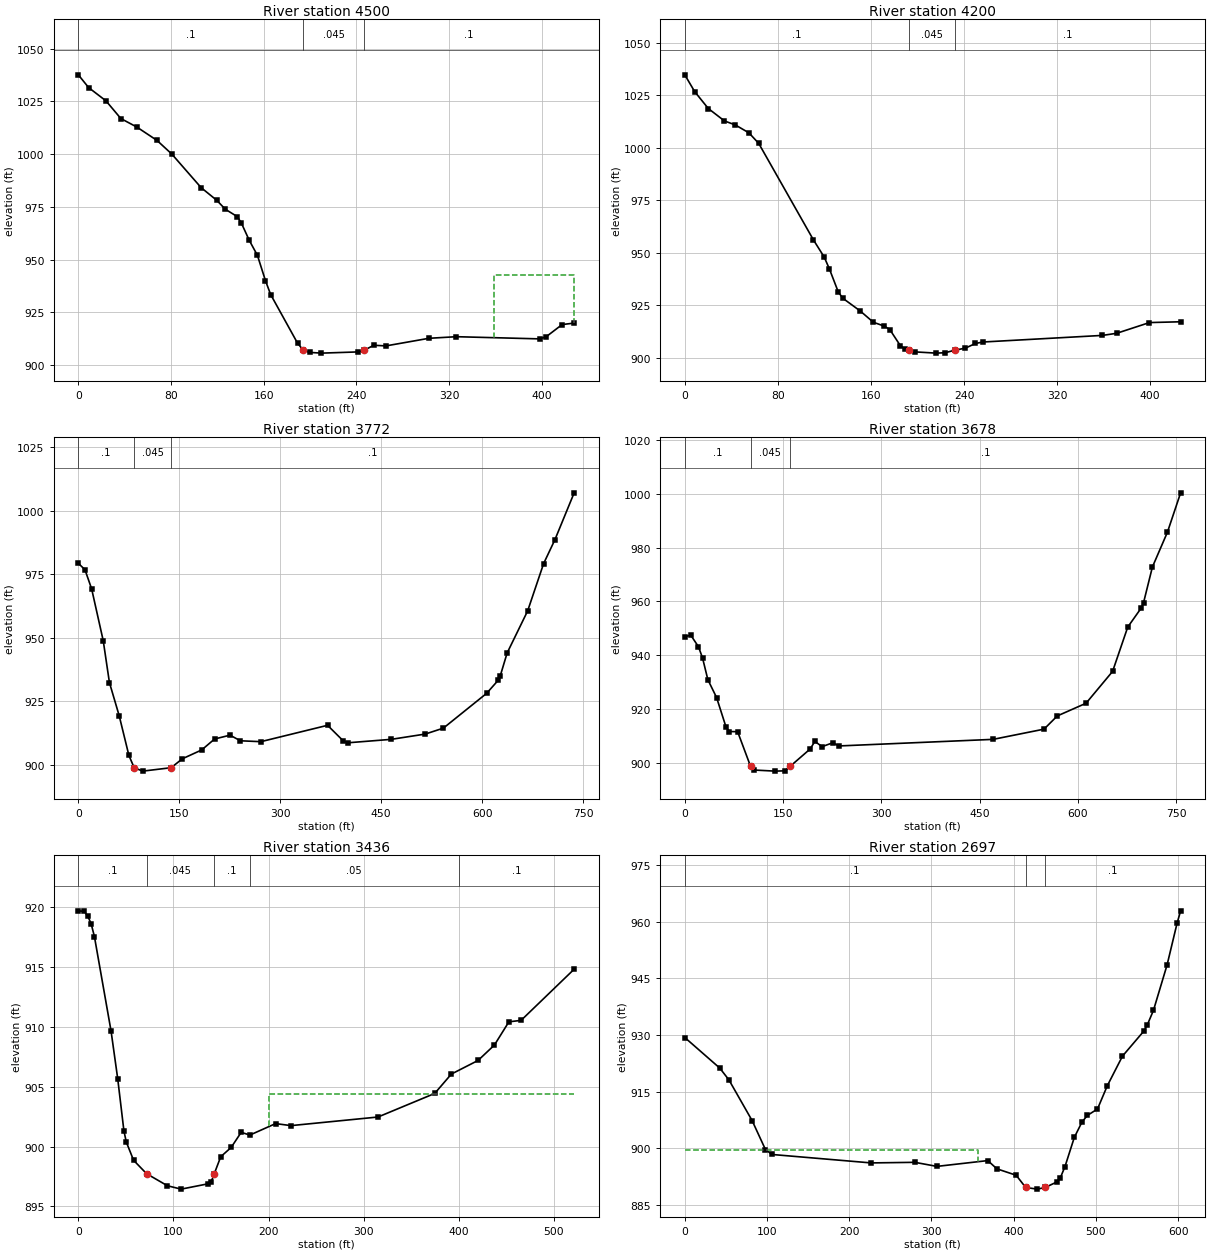
Type RM Length L Ch R = 1 ,4500    ,307,300,288.8
XS GIS Cut Line= 6
1672500.04299109461360.4548735021672528.36576909 461443.24407801
1672552.64262342461514.2065345051672585.01198126 461608.82281509
1672603.47946401461681.7724723371672621.90068701461770.107925594
#Sta/Elev= 30
       0 1037.55     8.9  1031.5    23.9  1025.2    36.7 1016.84    50.5 1012.81
    67.9 1006.48    80.7 1000.01     106  984.11   119.5  978.11   126.8  973.91
   137.2  970.38   140.7  967.37   147.6  959.09   154.6  952.02   161.5  940.09
     166  933.49   189.2  910.47  194.21907.0749   199.6  906.07   209.9  905.72
   241.3  906.29  246.62907.0747   255.1  909.44   265.5  909.14   302.7  912.75
   326.4   913.5   398.1  912.47   403.6  913.38   417.6  919.25     428  919.95
#Mann= 3 ,-1,0
       0      .1       0  194.21    .045       0  246.62      .1       0
#XS Ineff= 2 , 0
                          358.39          942.82
Permanent Ineff=
       F       F
Bank Sta=194.21,246.62
XS Rating Curve= 0 ,0
Exp/Cntr(USF)=0,0
Exp/Cntr=0.3,0.1

Type RM Length L Ch R = 1 ,4200    ,467,427.6,405.5
XS GIS Cut Line= 6
1672180.66698943461563.604729667 1672237.8250116461629.855909511
1672286.81769575461686.6422132551672352.14105593461762.357941091
1672406.75380759461814.2958293411672473.15262492461872.574584171
#Sta/Elev= 30
       0 1034.69     8.5 1026.69    20.2 1018.65    34.1 1012.73    43.4 1010.84
    55.1 1007.07    63.5 1002.08   110.6  956.06   119.8  947.95   124.2  942.41
   131.8  931.48   135.7  928.36   150.8  922.24   162.1  916.87   171.4  915.06
   176.2  913.42   185.3  905.73   189.2  904.04  192.45   903.6   197.8  902.77
   216.1  902.18   223.8  902.37  232.24903.5995   241.2  904.56   249.8  906.77
   256.2  907.47     359  910.62   371.2  911.62   399.4  916.73   426.2  917.11
#Mann= 3 ,-1,0
       0      .1       0  192.45    .045       0  232.24      .1       0
Bank Sta=192.45,232.24
XS Rating Curve= 0 ,0
Exp/Cntr(USF)=0,0
Exp/Cntr=0.3,0.1

Type RM Length L Ch R = 1 ,3772    ,88.1,94.1,87.6
XS GIS Cut Line= 5
1671981.55881543462089.5783088161672021.54243005462108.770443836
1672152.68868602462048.7950218981672271.83985761461975.225170987
 1672667.6776424462074.384535258
#Sta/Elev= 30
       0   979.3     9.8  976.83    19.8  969.23      37  948.85    46.2   932.4
    60.7  919.34    75.1  903.74   82.93898.8889    95.7  897.54  137.92898.8898
   154.5  902.39   183.3  905.88   202.5  910.19   225.4  911.69   240.8  909.48
   271.2  909.13   370.3  915.57   393.6  909.45   400.4  908.69     465  910.05
   515.4  912.12   542.4  914.46   606.7  928.16   623.6  933.23     627  935.12
   637.1  944.02   667.6  960.59   691.3  979.19   708.2  988.66   736.7 1007.05
#Mann= 3 ,-1,0
       0      .1       0   82.93    .045       0  137.92      .1       0
Bank Sta=82.93,137.92
XS Rating Curve= 0 ,0
Exp/Cntr(USF)=0,0
Exp/Cntr=0.3,0.1

Type RM Length L Ch R = 1 ,3678    ,221.9,242.2,266.3
XS GIS Cut Line= 5
1671965.56536957462220.3247286411672155.88737519462138.758154805
 1672240.6526382462069.1866653571672303.02707701 462024.00518083
1672655.68255801462109.170279982
#Sta/Elev= 30
       0  946.91     9.2  947.41    20.9  943.11    27.1  938.93    35.2  930.87
    48.5  924.24    62.8  913.34    67.7   911.6    80.6  911.55  100.38898.6325
   105.6  897.29   137.7  896.88   152.7  896.99  160.59898.6314   191.3  905.12
   198.4  907.93   209.5  905.99     226  907.44     235  906.24   470.4  908.69
   548.1  912.49   568.3   917.4   612.2  922.12   652.7  933.96   675.8  950.43
   696.6  957.61   699.9  959.49   713.4  972.75   736.4  985.75   756.5 1000.36
#Mann= 3 ,-1,0
       0      .1       0  100.38    .045       0  160.59      .1       0
Bank Sta=100.38,160.59
XS Rating Curve= 0 ,0
Exp/Cntr(USF)=0,0
Exp/Cntr=0.3,0.1

Type RM Length L Ch R = 1 ,3436    ,670,739,765.3
XS GIS Cut Line= 2
1671922.16615167 462366.248165251672409.69688937462550.426443938
#Sta/Elev= 30
       0  919.71     6.3  919.66     9.9  919.26    13.4  918.65    16.9  917.56
    34.4  909.66    41.4  905.67    47.9  901.32    50.4  900.38    58.1  898.85
   71.73897.7316    93.7  896.72   108.1  896.44   136.1  896.88   139.5  897.03
  142.92897.7332   149.7  899.15   160.7  899.93   171.2  901.19   180.3  900.96
   207.4  901.92   223.5  901.75     315  902.47   374.6  904.44   392.1  906.06
   420.2   907.2   437.4  908.49   452.6  910.43   465.4  910.55   521.2  914.83
#Mann= 5 ,-1,0
       0      .1       0   71.73    .045       0  142.92      .1       0
     180     .05       0     400      .1       0
#XS Ineff= 2 , 0
                          200.58          904.43
Permanent Ineff=
       F       F
Bank Sta=71.73,142.92
XS Rating Curve= 0 ,0
Exp/Cntr(USF)=0,0
Exp/Cntr=0.3,0.1

Type RM Length L Ch R = 1 ,2697    ,291.4,297.1,298.8
XS GIS Cut Line= 3
 1671928.9833011462304.8616762351671914.21880877462344.702898971
1671458.62344498462671.279652315
#Sta/Elev= 30
       0  929.34    42.5  921.24    53.7  918.09    81.9  907.29    98.1  899.62
   106.1  898.32   226.7  896.08   279.7  896.24   306.6  895.16   368.5   896.7
   379.5  894.52     403  892.81  414.56  889.57   428.7  889.13   438.3  889.57
   452.4  891.02   456.8  892.18   462.4  895.13   473.7  902.84     483  906.91
   489.6  908.68   501.9  910.38   513.8  916.53   532.3  924.41   558.2  931.03
   562.3   932.6     570  936.57   586.5  948.57   598.6  959.58     603  962.94
#Mann= 3 ,-1,0
       0      .1       0  414.56    .045       0   438.3      .1       0
#XS Ineff= 2 , 0
          356.82  899.61
Permanent Ineff=
       F       F
Bank Sta=414.56,438.3
XS Rating Curve= 0 ,0
Exp/Cntr(USF)=0,0
Exp/Cntr=0.3,0.1

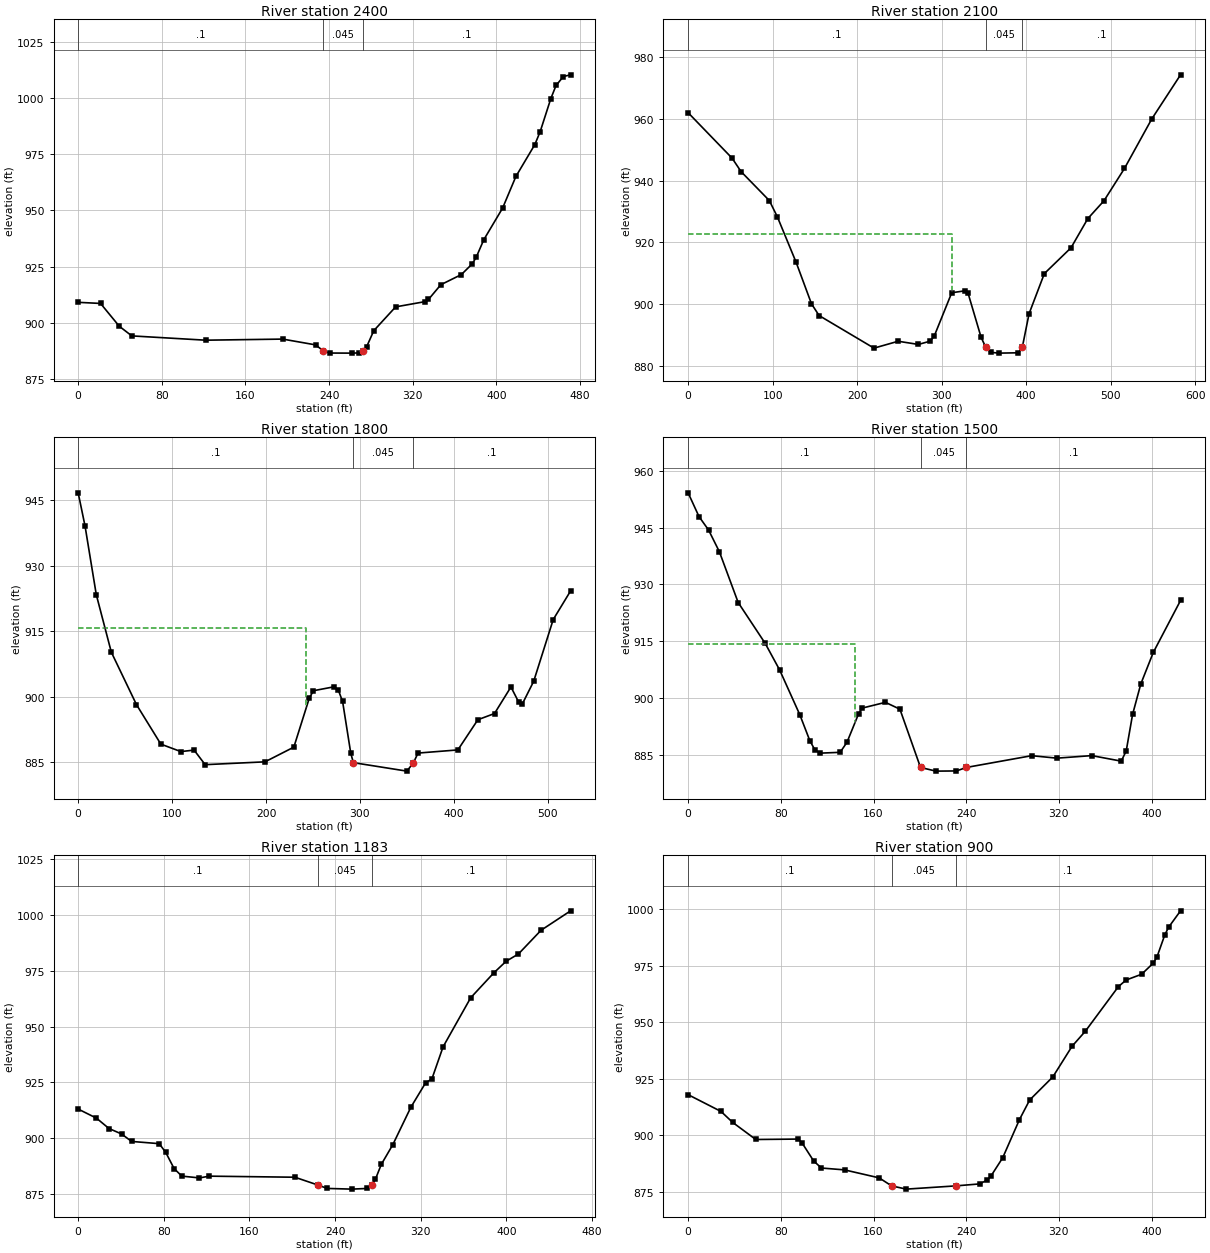
Type RM Length L Ch R = 1 ,2400    ,308.7,300,289.2
XS GIS Cut Line= 6
1671711.19227083462183.970478554 1671599.6094245462257.043631509
1671528.94946083462282.1872820111671434.80693258462315.909655511
 1671364.2004465462341.2015996721671281.82561126462370.709086582
#Sta/Elev= 30
       0  909.08    21.4  908.59    39.3  898.46    51.3  894.16   121.9  892.25
   195.6  892.74     227  890.17234.3213887.5514   240.9  886.54   261.8   886.5
   268.8   886.6272.6913 887.584   275.8  889.26   282.7  896.48   303.6  907.06
   331.7  909.39     335  910.37   346.8  916.91   366.4  921.41   376.8  926.16
   380.6  929.07   387.9  936.92   405.9  950.99   418.6  965.04   436.7  979.21
   441.8  984.95     452  999.67     457 1005.49     464 1009.47   470.9 1010.22
#Mann= 3 ,-1,0
       0      .1       0234.3213    .045       0272.6913      .1       0
Bank Sta=234.3213,272.6913
XS Rating Curve= 0 ,0
Exp/Cntr(USF)=0,0
Exp/Cntr=0.3,0.1

Type RM Length L Ch R = 1 ,2100    ,295.7,300,310.9
XS GIS Cut Line= 6
1671600.55604175461771.5583091461671431.72458968461949.453039333
1671380.19877408462003.9516180011671311.49713984 462076.61584276
1671259.97132425462131.1144214271671199.85759935462194.695659086
#Sta/Elev= 30
       0  962.02    52.1  947.26    62.7  942.91    96.1  933.53   105.6  928.27
   127.9  913.46     146  900.06     155  896.25     220  885.68   248.6  887.91
   272.5  886.88   286.1  887.91   291.1  889.46     312  903.64   328.2  904.29
   331.3  903.51   346.8  889.15352.3563885.9058   358.3  884.32   367.7  884.06
   390.9  884.17395.4863885.9177   403.5  896.82   421.6  909.85   453.2  918.23
   473.1   927.7   492.2  933.47   516.4  943.93   548.7  959.97   582.8   974.3
#Mann= 3 ,-1,0
       0      .1       0352.3563    .045       0395.4863      .1       0
#XS Ineff= 2 , 0
          312.29  922.55
Permanent Ineff=
       F       F
Bank Sta=352.3563,395.4863
XS Rating Curve= 0 ,0
Exp/Cntr(USF)=0,0
Exp/Cntr=0.3,0.1

Type RM Length L Ch R = 1 ,1800    ,304.5,300,288.7
XS GIS Cut Line= 6
1671379.68765638461665.848528776  1671226.183006461772.085940003
1671164.25498025 461814.393270091671081.68427926461870.803262249
1671019.75625351461913.1105923351670947.50705418461962.469417512
#Sta/Elev= 30
       0  946.71     7.3  939.13    19.3  923.36    35.3  910.19    62.1  898.16
      88  889.12   109.3  887.41   123.4  887.75   135.2  884.41   198.9  885.06
   229.6  888.43   246.1   899.7   250.5  901.36     272  902.24   276.8  901.58
   281.5  898.89   290.2  887.02  292.95884.8746   349.9  882.93  356.84884.8284
   361.8  887.07   404.2  887.79   425.5  894.71   443.2  896.13   460.7  902.22
     469  898.72     473   898.4   484.9  903.51   505.7  917.67   524.2  924.23
#Mann= 3 ,-1,0
       0      .1       0  292.95    .045       0  356.84      .1       0
#XS Ineff= 2 , 0
          242.85   915.8
Permanent Ineff=
       F       F
Bank Sta=292.95,356.84
XS Rating Curve= 0 ,0
Exp/Cntr(USF)=0,0
Exp/Cntr=0.3,0.1

Type RM Length L Ch R = 1 ,1500    ,301.7,317.3,316.1
XS GIS Cut Line= 6
1671047.01079218461476.6692080051670989.54240318 461542.65103142
1670940.28364342461599.2073487491670874.60529709461674.615006343
1670825.34653734461731.1713236721670770.03726476461799.033392668
#Sta/Elev= 30
       0   954.2     9.4  947.92    17.7  944.35      27  938.62    43.2  925.21
    66.5  914.42      79  907.38    96.4  895.55   105.1  888.65   109.4  886.28
   113.8  885.39   131.2  885.61   137.1  888.26   147.1  895.77   150.2   897.3
   170.3  898.82   182.8  897.01  200.58881.6142   213.9  880.64   231.6  880.69
  240.19881.6161   296.5  884.72   318.3  884.07   348.4  884.74   373.8  883.28
   378.1  885.96   383.6  895.62   390.7  903.68   401.5  912.03     425  925.75
#Mann= 3 ,-1,0
       0      .1       0  200.58    .045       0  240.19      .1       0
#XS Ineff= 2 , 0
          143.87  914.31
Permanent Ineff=
       F       F
Bank Sta=200.58,240.19
XS Rating Curve= 0 ,0
Exp/Cntr(USF)=0,0
Exp/Cntr=0.3,0.1

Type RM Length L Ch R = 1 ,1183    ,266.4,282.7,290.6
XS GIS Cut Line= 2
1670822.65006388 461378.031463731670452.57121012461650.997050098
#Sta/Elev= 30
       0  913.07    17.1  908.99    28.8  904.35    40.5  901.92    49.9  898.57
    75.7  897.57    81.8  893.65    89.6  886.41    96.8  883.04   113.3  882.23
   122.5  883.02   202.4  882.54  223.81879.0624   232.6  877.52   255.5  877.21
   269.3   877.5  274.26879.0615   277.6  881.61   283.1  888.27   293.9  897.15
   310.7  913.86   324.4  924.74   330.4  926.61   340.8  940.92   366.6  962.91
   388.1  974.01   399.7  979.26   411.2  982.52   432.3  993.13   459.9 1001.84
#Mann= 3 ,-1,0
       0      .1       0  223.81    .045       0  274.26      .1       0
Bank Sta=223.81,274.26
XS Rating Curve= 0 ,0
Exp/Cntr(USF)=0,0
Exp/Cntr=0.3,0.1

Type RM Length L Ch R = 1 ,900     ,303.3,300,299.3
XS GIS Cut Line= 6
1670748.74006325461226.656912759 1670662.5443695461241.706751421
1670588.66197135461254.6066600081670490.15232584461271.806756839
1670416.27025576461284.7066654261670330.07423392461299.756504089
#Sta/Elev= 30
       0  917.99    28.4  910.57    38.4  905.75    58.4  898.17      95  898.36
    98.3  896.69   108.3  888.72     115  885.56     135  884.74   164.9  881.21
   175.6877.6706   188.3  876.23  231.14877.6689   251.5  878.53   258.2  880.24
   261.5  882.12   271.5  890.08     286     907   294.8  915.64   314.8  925.85
   331.4  939.41   342.8  946.01   371.4  965.78   378.1  968.69   391.4  971.22
   401.4  976.11   404.7  978.92   411.4  988.61   414.7  992.01     425  999.26
#Mann= 3 ,-1,0
       0      .1       0   175.6    .045       0  231.14      .1       0
Bank Sta=175.6,231.14
XS Rating Curve= 0 ,0
Exp/Cntr(USF)=0,0
Exp/Cntr=0.3,0.1

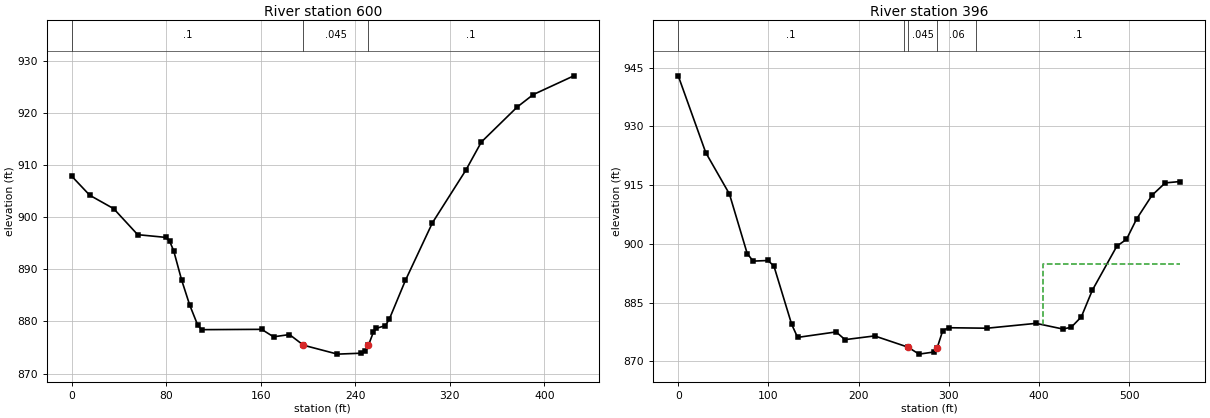
Type RM Length L Ch R = 1 ,600     ,201.8,204,208.9
XS GIS Cut Line= 6
1670676.49611326460920.1214365961670591.60881583460941.343178928
1670518.84813459460959.5334312621670421.83389293 460983.78731975
1670349.07321167461001.9775720831670264.18558617461023.199314415
#Sta/Elev= 30
       0  907.82    15.2  904.18    35.5   901.6    55.8  896.62    79.5   896.1
    82.9  895.34    86.3  893.51      93  887.92    99.8  883.15   106.5  879.34
   109.9  878.41   160.7  878.47   170.8  877.04   184.3  877.47  196.15875.4296
   224.9  873.72   245.2   873.9   248.6  874.28  251.14875.4296   255.3  877.92
   257.8  878.66   265.5  879.19   268.9  880.48   282.4  887.84   305.3   898.9
   333.6  908.99   346.7  914.38   377.1   921.1   390.6  923.47     425  927.07
#Mann= 3 ,-1,0
       0      .1       0  196.15    .045       0  251.14      .1       0
Bank Sta=196.15,251.14
XS Rating Curve= 0 ,0
Exp/Cntr(USF)=0,0
Exp/Cntr=0.3,0.1

Type RM Length L Ch R = 1 ,396     ,,,
XS GIS Cut Line= 3
1670695.42315648460757.3713461381670310.88245117460780.778171679
1670241.96606911 460938.00516267
#Sta/Elev= 30
       0  942.91    30.5  923.31    56.8  912.72    76.5  897.53    83.1  895.59
    99.5  895.75   106.1  894.35   125.8  879.46   132.4  876.11   175.1  877.51
     185  875.54   217.8  876.49  254.82873.6238   267.1  871.84   283.6  872.38
  287.32873.5311   293.4  877.84     300  878.58   342.7  878.46   396.9   879.7
   426.6  878.25   435.9   878.7   447.1  881.35   459.3  888.15   486.5  899.41
   497.2  901.16   508.4  906.34   525.5   912.4   540.2  915.57   556.9  915.92
#Mann= 5 ,-1,0
       0      .1       0     250     .06       0  254.82    .045       0
  287.32     .06       0     330      .1       0
#XS Ineff= 2 , 0
                           404.3          894.77
Permanent Ineff=
       F       F
Bank Sta=254.82,287.32
XS Rating Curve= 0 ,0
Exp/Cntr(USF)=0,0
Exp/Cntr=0.3,0.1
LCMann Table=0

Chan Stop Cuts=-1
Use User Specified Reach Order=0
Composite Channel Slope=5